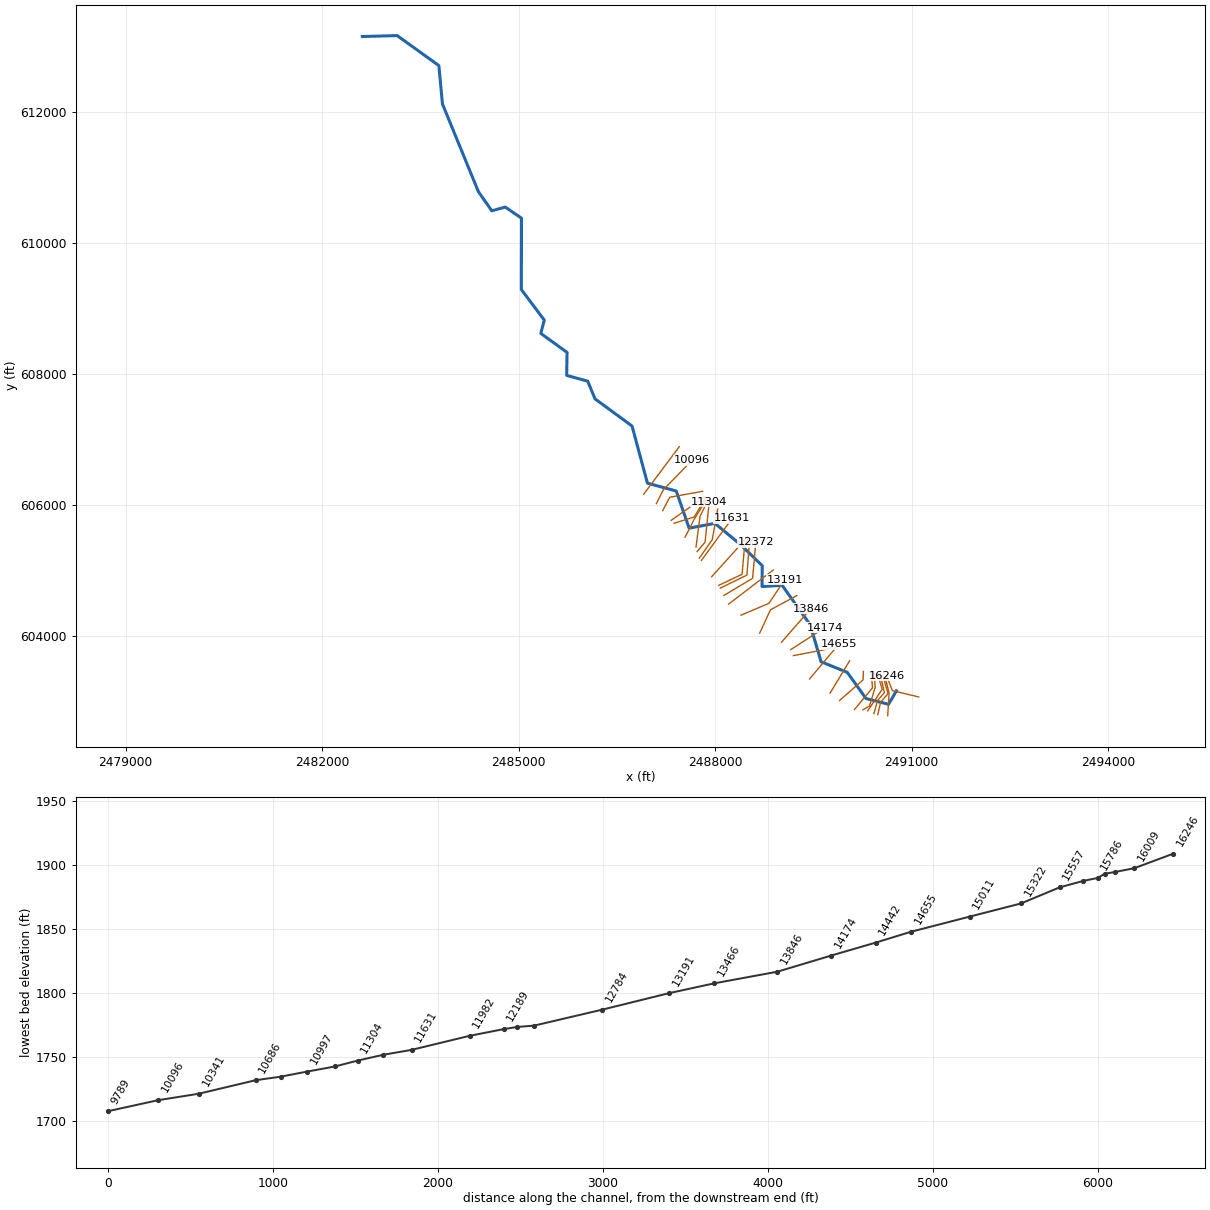
--- STONYRN1.prj (project) ---

Proj Title=STONYRN1
Current Plan=p01
Default Exp/Contr=0,0
English Units
Geom File=g01
Flow File=f01
Plan File=p01
BEGIN DESCRIPTION:
Stream Name: Stony Run 1
Flood Zone: Approximate
Pendleton County, West Virginia
HEC-RAS Version: 5.0.7
Hydrology Method:
Regression equation
END DESCRIPTION:
DSS Export Rating Curves= 0
DSS Export Rating Curve Sorted= 0
DSS Export Volume Flow Curves= 0
DXF OffsetX= 0
DXF OffsetY= 0
DXF ScaleX= 0
DXF ScaleY= 0

--- STONYRN1.p01 (plan) ---

Plan Title=Floodplain
Program Version=5.07
Short Identifier=Floodplain
Geom File=g01
Flow File=f01
Subcritical Flow
K Sum by GR= 0
Std Step Tol= 0.01
Critical Tol= 0.01
Num of Std Step Trials= 20
Max Error Tol= 0.3
Flow Tol Ratio= 0.001
Split Flow NTrial= 30
Split Flow Tol= 0.02
Split Flow Ratio= 0.02
Log Output Level= 0
Friction Slope Method= 1
Unsteady Friction Slope Method= 2
Unsteady Bridges Friction Slope Method= 1
Parabolic Critical Depth
Global Vel Dist= 0 , 0 , 0
Global Log Level= 0
CheckData=True
Encroach Param=-1 ,0,0, 0
Mapping Interval=1HOUR
Computation Time Step Use Courant=        0
Computation Time Step Use Time Series=    0
Computation Time Step Count To Double=0
Computation Time Step Max Doubling=0
Computation Time Step Max Halving=0
Computation Time Step Residence Courant=0
Run HTab= 0
Run UNet= 0
Run Sediment= 0
Run PostProcess= 0
Run WQNet= 0
Run RASMapper= 0
UNET Theta= 0
UNET Theta Warmup= 0
UNET ZTol= 0
UNET ZSATol= 0
UNET MxIter= 0
UNET Max Iter WO Improvement= 0
UNET MaxInSteps= 0
UNET DtIC= 0
UNET DtMin= 0
UNET MaxCRTS= 0
UNET WFStab= 0
UNET SFStab= 0
UNET WFX= 1
UNET SFX= 1
UNET 1D Methodology=Finite Difference
UNET DSS MLevel= 1
UNET Pardiso=0
UNET DZMax Abort= 0
UNET Use Existing IB Tables= 0
UNET Froude Reduction=False
UNET Froude Limit= 0
UNET Froude Power= 0
UNET D1 Cores= 0
UNET D2 Coriolis=0
UNET D2 Cores= 0
UNET D2 Theta= 1
UNET D2 Theta Warmup= 1
UNET D2 Z Tol= 0.01
UNET D2 Volume Tol= 0.01
UNET D2 Max Iterations= 20
UNET D2 Equation= 0
UNET D2 RampUpFraction=0.1
UNET D2 TimeSlices= 1
UNET D2 BCVolumeCheck=0
UNET D1D2 MaxIter= 0
UNET D1D2 ZTol=0.01
UNET D1D2 QTol=0.1
UNET D1D2 MinQTol=1
Write IC File= 0
Write IC File at Fixed DateTime=0
Write IC File at Sim End=0
Echo Input=False
Echo Parameters=False
Echo Output=False
Write Detailed= 0
HDF Write Warmup=0
HDF Write Time Slices=0
HDF Flush=0
HDF Face Node Velocities=0
HDF Compression= 1
HDF Chunk Size= 1
HDF Spatial Parts= 1
HDF Use Max Rows=0
HDF Fixed Rows= 1
Calibration Method= 0
Calibration Iterations= 20
Calibration Max Change=0.05
Calibration Tolerance=0.2
Calibration Maximum=1.5
Calibration Minimum=0.5
Calibration Optimization Method= 1
WQ AD Non Conservative
WQ ULTIMATE=-1
WQ Max Comp Step=1HOUR
WQ Output Interval=15MIN
WQ Output Selected Increments= 0
WQ Output face flow=0
WQ Output face velocity=0
WQ Output face area=0
WQ Output face dispersion=0
WQ Output cell volume=0
WQ Output cell surface area=0
WQ Output cell continuity=0
WQ Output cumulative cell continuity=0
WQ Output face conc=0
WQ Output face dconc_dx=0
WQ Output face courant=0
WQ Output face peclet=0
WQ Output face adv mass=0
WQ Output face disp mass=0
WQ Output cell mass=0
WQ Output cell source sink temp=0
WQ Output nsm pathways=0
WQ Output nsm derived pathways=0
WQ Output MaxMinRange=-1
WQ Daily Max Min Mean=-1
WQ Daily Range=0
WQ Daily Time=0
WQ Create Restart=0
WQ Fixed Restart=0
WQ System Summary=0
WQ Write To DSS=0
WQ Use Fixed Temperature=0
Sorting and Armoring Iterations= 10
XS Update Threshold= 0.02
Bed Roughness Predictor= 0
Hydraulics Update Threshold= 0.02
Energy Slope Method= 1
Volume Change Method= 1
Sediment Retention Method= 0
XS Weighting Method= 0
Number of US Weighted Cross Sections= 1
Number of DS Weighted Cross Sections= 1
Upstream XS Weight=0
Main XS Weight=1
Downstream XS Weight=0
Number of DS XS's Weighted with US Boundary= 1
Upstream Boundary Weight= 1
Weight of XSs Associated with US Boundary= 0
Number of US XS's Weighted with DS Boundary= 1
Downstream Boundary Weight= 0.5
Weight of XSs Associated with DS Boundary= 0.5
Percentile Method= 0
Sediment Output Level= 3
Mass or Volume Output= 0
Output Increment Type= 1
Profile and TS Output Increment= 1
XS Output Flag= 0
XS Output Increment= 10
Write Gradation File= 0
Read Gradation Hotstart= 0
Write HDF5 File= 1
Write Binary Output= 1
Write DSS Sediment File= 0
SV Curve= 0
Specific Gage Flag= 0

--- STONYRN1.f01 (steady flow) ---

Flow Title=Flows
Program Version=5.07
Number of Profiles= 6
Profile Names=P100yr,P10yr,P25yr,P50yr,P500yr,P101yr
River Rch & RM=STONYRN1,Main            ,16246
     580     271     384     479     851     706
River Rch & RM=STONYRN1,Main            ,13466
     652     304     431     538     957     793
River Rch & RM=STONYRN1,Main            ,11631
     744     347     491     613    1093     905
River Rch & RM=STONYRN1,Main            ,5310
     828     385     546     683    1219    1008
Boundary for River Rch & Prof#=STONYRN1,Main            , 1
Up Type= 0
Dn Type= 3
Dn Slope=0.028458
Boundary for River Rch & Prof#=STONYRN1,Main            , 2
Up Type= 0
Dn Type= 3
Dn Slope=0.028458
Boundary for River Rch & Prof#=STONYRN1,Main            , 3
Up Type= 0
Dn Type= 3
Dn Slope=0.028458
Boundary for River Rch & Prof#=STONYRN1,Main            , 4
Up Type= 0
Dn Type= 3
Dn Slope=0.028458
Boundary for River Rch & Prof#=STONYRN1,Main            , 5
Up Type= 0
Dn Type= 3
Dn Slope=0.028458
Boundary for River Rch & Prof#=STONYRN1,Main            , 6
Up Type= 0
Dn Type= 3
Dn Slope=0.028458
DSS Import GetInterval= 0
DSS Import GetPeak= 0
DSS Import FillOption= 0

--- STONYRN1.g01 (geometry) ---

Geom Title=Geometry
Program Version=5.07

River Reach=STONYRN1        ,Main
Reach XY= 30
     2490766.074       603166.91      2490646.86      602961.698
     2490302.354      603049.211     2490016.285      603448.405
     2489616.988       603610.58     2489449.473      604175.874
     2489022.222      604777.297      2488715.09      604758.928
     2488718.358      605077.525     2488390.621      605395.427
     2487996.689      605723.192     2487602.486      605650.209
     2487405.877      606216.722     2486966.037      606336.628
     2486731.001      607208.976     2486165.824      607623.404
     2486054.035      607893.507     2485733.451      607982.413
     2485738.648       608333.35     2485338.291      608622.405
     2485390.784      608826.697      2485040.91      609292.979
2485043.80329707610381.800299356 2484795.1393489610551.146636825
2484590.07878458610494.344632124     2484385.997      610785.601
     2483836.567      612125.406     2483782.263      612710.833
     2483144.864      613169.101     2482613.867      613154.388

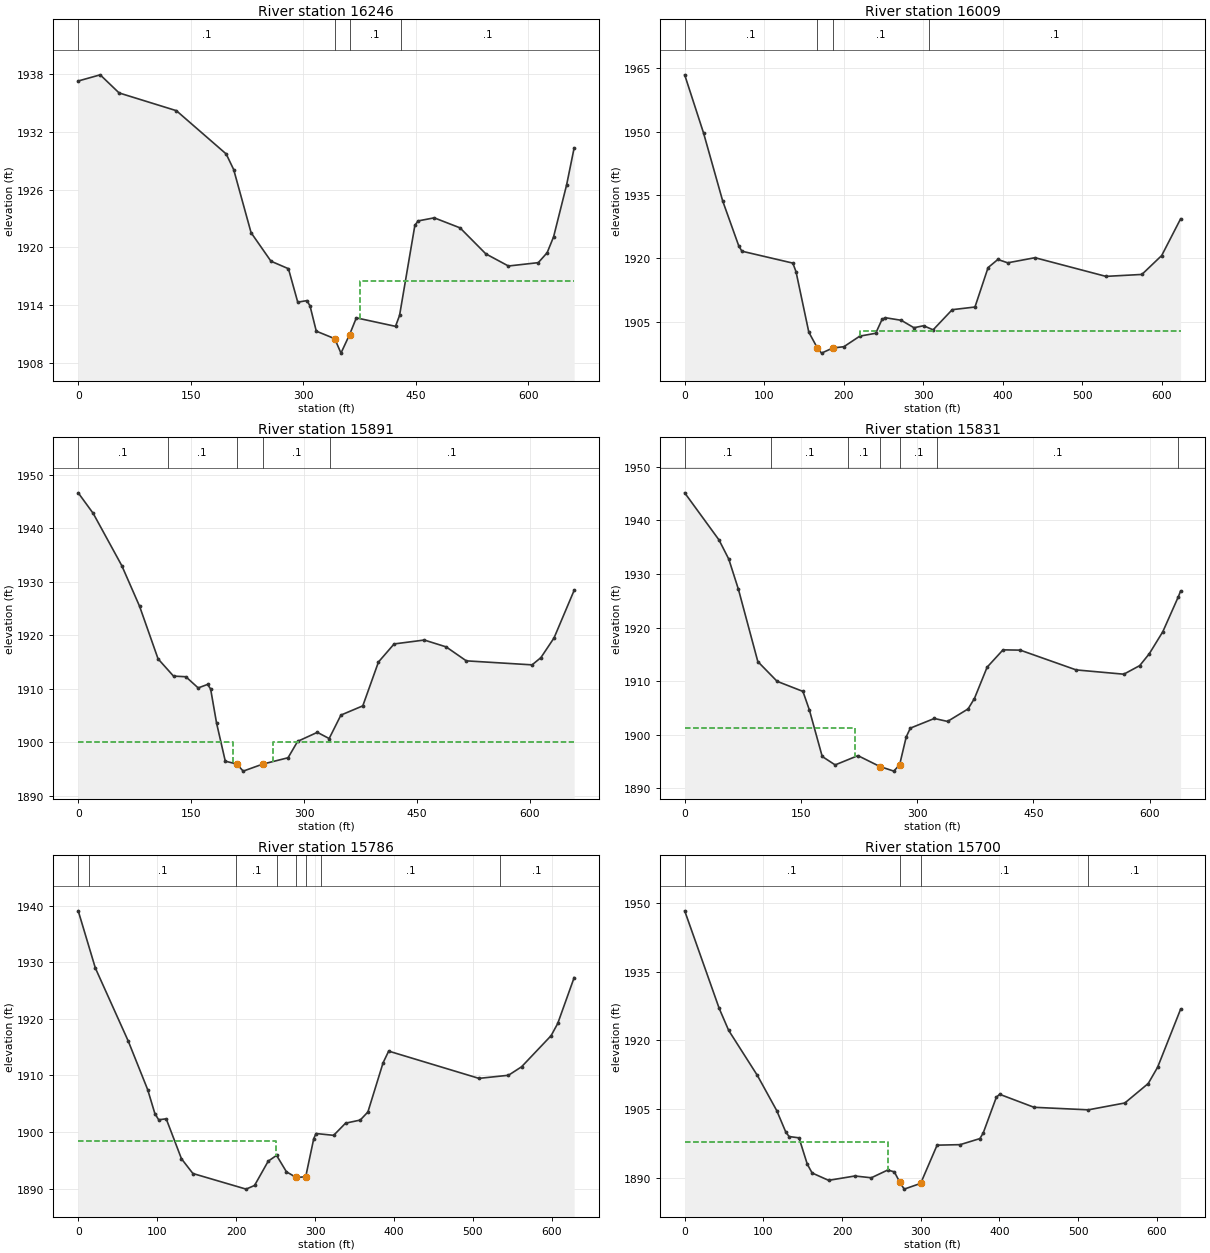
Type RM Length L Ch R = 1 ,16246   ,248.1,237.1,221.6
XS GIS Cut Line= 3
2491107.27023163603073.6692316322490705.32015816603170.038245205
2490614.19361725603400.325675561
#Sta/Elev= 30
       0 1937.27    29.3 1937.91    54.5 1936.03   130.8 1934.19   197.2  1929.7
   207.2 1928.08   230.4 1921.53   256.9 1918.57   280.2 1917.79   292.6 1914.32
   304.9 1914.48     309 1913.92   317.3 1911.31   341.9 1910.53   350.2 1909.03
   361.6 1910.94   370.7 1912.69   422.9 1911.81   428.3 1912.94   448.7 1922.29
     453 1922.75   474.5 1923.07   508.9 1922.03   543.3 1919.33   573.4 1918.07
   613.2 1918.42     625 1919.45   633.6  1921.1   650.9 1926.47     661 1930.33
#Mann= 4 ,-1 , 0
       0      .1       0   341.9    .045       0   361.6      .1       0
  430.18      .1       0
#XS Ineff= 2 , 0
                          375.46         1916.48
Permanent Ineff=
       F       F
Bank Sta=341.9,361.6
XS Rating Curve= 0 ,0
Exp/Cntr=0.3,0.1

Type RM Length L Ch R = 1 ,16009   ,123,118.4,108.2
XS GIS Cut Line= 3
2490633.19683909602787.1376704052490654.90370788   603130.217972
 2490588.9778489  603402.1713034
#Sta/Elev= 30
       0 1963.43    23.8 1949.62    47.8 1933.58    67.9 1923.01    71.9  1921.7
     136 1918.88     140 1916.85   156.1 1902.53   166.81898.816   172.1 1897.58
   186.3  1898.8   200.2  1899.1   220.2  1901.6   240.2 1902.28   248.2 1905.57
   252.3 1905.96   272.3 1905.35   288.3 1903.59   300.4 1904.06   312.4 1903.09
   336.4 1907.86     365 1908.49   381.5 1917.82   393.8 1919.74   406.2 1918.95
   440.5 1920.16   529.7 1915.74   574.9  1916.2   599.8 1920.67   623.6 1929.36
#Mann= 4 ,-1 , 0
       0      .1       0   166.8    .045       0   186.3      .1       0
  307.69      .1       0
#XS Ineff= 2 , 0
                          220.38         1902.89
Permanent Ineff=
       F       F
Bank Sta=166.8,186.3
XS Rating Curve= 0 ,0
Exp/Cntr=0.5,0.3

Type RM Length L Ch R = 1 ,15891   ,56.3,59.4,53.4
XS GIS Cut Line= 4
2490481.78198412602803.4983638782490524.91617996602991.123220684
2490638.55545343 603126.202054082490557.56901923603404.554104687
#Sta/Elev= 30
       0 1946.59    19.9 1942.75    57.9 1932.98    81.5  1925.4   106.1 1915.56
   126.6 1912.34     143 1912.22   159.4 1910.13   171.8 1910.78   175.9 1909.95
   183.8 1903.57   195.4 1896.44   210.7 1895.91   219.2 1894.58   245.1 1895.89
   278.8 1897.08   291.5 1900.14   317.7 1901.83   333.4 1900.67     349 1905.05
   378.1 1906.78   398.9 1914.97   419.7 1918.35   459.8 1919.08   488.8  1917.8
   515.6 1915.19     603 1914.44   614.7 1915.79   632.2 1919.48   658.9 1928.37
#Mann= 5 ,-1 , 0
       0      .1       0  118.72      .1       0   210.7    .045       0
   245.1      .1       0  334.59      .1       0
#XS Ineff= 2 , 0
          206.13    1900  258.28            1900
Permanent Ineff=
       F       F
Bank Sta=210.7,245.1
XS Rating Curve= 0 ,0
Exp/Cntr=0.5,0.3

Type RM Length L Ch R = 1 ,15831   ,45.7,45.1,45.7
XS GIS Cut Line= 4
2490422.69759108 602820.157567282490480.19383388603021.657886993
 2490583.2315621 603138.447779942490522.74354757603406.425843013
#Sta/Elev= 30
       0 1945.15    44.3 1936.36    56.9 1932.79    69.4 1927.13    94.4 1913.67
   119.3 1909.99   152.6 1908.11   160.9 1904.66   177.5 1895.97   194.2  1894.4
   223.6 1896.13   251.9  1894.1   269.9 1893.24   277.4 1894.44   285.9 1899.63
   291.2 1901.26   322.2 1903.06   339.2 1902.51   365.7 1904.84   373.9 1906.78
   390.3 1912.63   410.8 1915.86     433 1915.81   505.2 1912.12   566.7 1911.32
   587.2 1912.92   599.5 1915.12     617 1919.24   637.1 1925.78     640 1926.85
#Mann= 7 ,-1 , 0
       0      .1       0  111.88      .1       0  210.28      .1       0
   251.9    .045       0   277.4      .1       0  326.04      .1       0
   637.1      .1       0
#XS Ineff= 2 , 0
          220.25 1901.36
Permanent Ineff=
       F       F
Bank Sta=251.9,277.4
XS Rating Curve= 0 ,0
Exp/Cntr=0.5,0.3

Type RM Length L Ch R = 1 ,15786   ,84.4,85.7,83.2
XS GIS Cut Line= 3
2490329.25466101602862.304906546 2490548.6268502603188.792422495
2490485.21457676  603415.0199926
#Sta/Elev= 30
       0 1939.11    21.7    1929    63.4 1916.08      88  1907.5    97.1 1903.28
   101.9 1902.17   111.5 1902.34   130.8 1895.28   145.3 1892.67   212.7 1889.91
   223.4 1890.56   240.7 1894.85   251.3 1895.88   263.8 1892.97   276.31891.966
   288.21892.097   298.4 1898.84   301.3 1899.74   323.6 1899.42   338.7 1901.57
   357.3 1902.12     367 1903.55   386.2 1912.23   393.3 1914.31   507.7 1909.49
   545.1 1910.04   561.7 1911.54   599.1 1917.04   607.5  1919.2   628.3 1927.31
#Mann= 8 ,-1 , 0
       0      .1       0   13.61      .1       0   200.1      .1       0
  251.38      .1       0   276.3    .045       0   288.2      .1       0
  307.77      .1       0  534.34      .1       0
#XS Ineff= 2 , 0
          250.33 1898.45
Permanent Ineff=
       F       F
Bank Sta=276.3,288.2
XS Rating Curve= 0 ,0
Exp/Cntr(USF)=0,0
Exp/Cntr=0.3,0.1

Type RM Length L Ch R = 1 ,15700   ,149.9,143.5,134.8
XS GIS Cut Line= 4
2490254.53952147602876.6725072722490355.49066748602935.897006778
2490441.42955294 603218.737088482490429.01953719603436.005586219
#Sta/Elev= 30
       0 1948.22    43.9 1926.97    55.9  1922.2    92.4 1912.39     117 1904.74
   128.5 1900.07   132.7  1899.1   145.3 1898.81   155.8 1893.09     162 1891.16
   182.9 1889.56   216.3 1890.51   237.2 1890.12   258.1 1891.81   266.5  1891.4
   273.11889.244     279 1887.65   299.9  1888.9   320.8 1897.22   350.1 1897.33
   375.2 1898.65   379.4 1899.86   396.1 1907.65   400.3 1908.29     444 1905.46
     513 1904.91   559.4  1906.4   589.1 1910.63   601.1 1914.19   630.3 1926.82
#Mann= 4 ,-1 , 0
       0      .1       0   273.1    .045       0   299.9      .1       0
     513      .1       0
#XS Ineff= 2 , 0
           258.9 1897.96
Permanent Ineff=
       F       F
Bank Sta=273.1,299.9
XS Rating Curve= 0 ,0
Exp/Cntr(USF)=0,0
Exp/Cntr=0.3,0.1

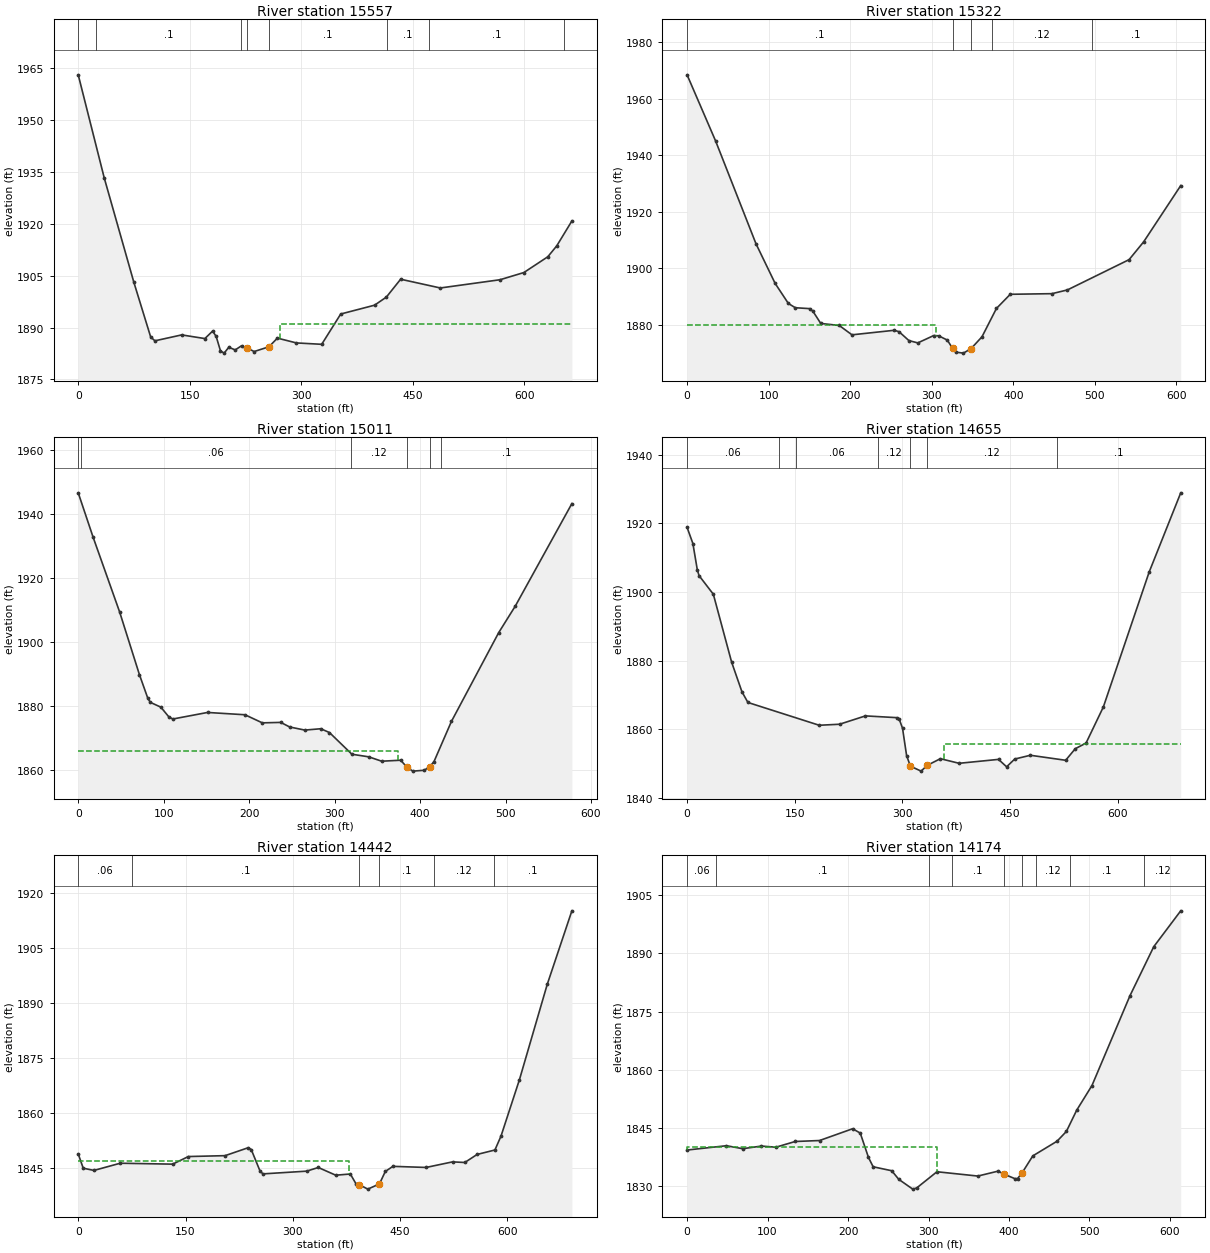
Type RM Length L Ch R = 1 ,15557   ,236,234.9,230.5
XS GIS Cut Line= 3
2490124.52031922602879.7650088622490401.49359664603213.677743581
2490381.89184418  603443.2275418
#Sta/Elev= 30
       0 1963.07      35 1933.26    74.8 1903.12    97.5 1887.26   103.2 1886.16
   139.2 1887.87   170.4 1886.81   180.8 1888.97   185.6 1887.43   191.4 1883.26
   196.3  1882.6   202.6  1884.3   211.2 1883.53   219.7 1884.72   227.5 1884.05
   236.7 1883.06   256.6 1884.43     268 1886.94   293.5 1885.55   327.6 1885.15
   353.2 1893.91   398.7 1896.46   414.6  1898.8   433.8 1903.97   487.2 1901.44
   567.5 1903.82   599.6  1905.9   631.8 1910.46   643.8  1913.6   664.2 1920.81
#Mann= 8 ,-1 , 0
       0      .1       0   23.55      .1       0  219.43      .1       0
   227.5    .045       0   256.6      .1       0  415.31      .1       0
  472.41      .1       0  653.15      .1       0
#XS Ineff= 2 , 0
                           272.1         1890.96
Permanent Ineff=
       F       F
Bank Sta=227.5,256.6
XS Rating Curve= 0 ,0
Exp/Cntr=0.3,0.1

Type RM Length L Ch R = 1 ,15322   ,304.5,310.7,313.2
XS GIS Cut Line= 3
2489898.57028121603019.810460905 2490257.4503481603333.761934588
2490262.77160767603462.147079613
#Sta/Elev= 30
       0 1968.48    35.1 1944.98    84.5 1908.67     108 1894.63   124.2 1887.54
   132.7 1886.03   150.5 1885.71   154.4 1884.75   163.9 1880.47   186.6 1879.75
   202.2 1876.44   253.8 1878.04   259.8 1877.57     272  1874.4   282.9 1873.58
   302.4 1876.18   308.5 1876.09   319.1 1874.57   325.5 1871.66   329.7 1870.31
   338.8 1869.96   348.1 1871.53   361.6 1875.74   379.3 1885.77   396.3 1890.79
   447.4 1891.01   466.4 1892.34     542 1903.06   559.9 1909.38   605.3 1929.27
#Mann= 5 ,-1 , 0
       0      .1       0   325.5    .045       0   348.1      .1       0
  374.29     .12       0  495.92      .1       0
#XS Ineff= 2 , 0
          305.77    1880
Permanent Ineff=
       F       F
Bank Sta=325.5,348.1
XS Rating Curve= 0 ,0
Exp/Cntr=0.3,0.1

Type RM Length L Ch R = 1 ,15011   ,356.2,356.3,353.5
XS GIS Cut Line= 2
2489753.61999439603132.2106485692490053.03347497603626.092865462
#Sta/Elev= 30
       0 1946.65    17.3 1932.87    48.5 1909.37    71.6 1889.83    81.4 1882.45
    84.3 1881.17    96.7 1879.65     106 1876.63   110.7 1875.95   151.3    1878
   195.1 1877.28   215.4 1874.75     237 1874.89   247.4 1873.46   265.1 1872.49
   283.8 1872.91     294 1871.71   320.2 1864.94   339.9 1864.13   355.1 1862.76
   377.3 1863.07   384.3 1860.97   391.4 1859.66   404.7 1859.92   411.1 1860.98
   416.3 1862.66   436.7 1875.21     492 1902.96   511.4 1911.25   577.6 1943.28
#Mann= 6 ,-1 , 0
       0      .1       0    3.08     .06       0  319.56     .12       0
   384.3    .045       0   411.1     .12       0  425.05      .1       0
#XS Ineff= 2 , 0
          374.16    1866
Permanent Ineff=
       F       F
Bank Sta=384.3,411.1
XS Rating Curve= 0 ,0
Exp/Cntr=0.3,0.1

Type RM Length L Ch R = 1 ,14655   ,219.3,213.1,203
XS GIS Cut Line= 2
2489441.53881481603348.5787475562489884.15663608603875.366515164
#Sta/Elev= 30
       0 1918.79     8.1 1914.08    14.3 1906.38    16.7 1904.73    36.6 1899.31
    62.1 1879.52    76.5 1870.88    84.8 1867.78   184.2 1861.14   212.6 1861.44
   248.6 1863.87   292.1 1863.36   295.6 1862.97   300.3 1860.28     306  1852.3
   311.3 1849.22   326.2 1847.78   334.7 1849.46   353.1  1851.4   379.2 1850.06
   434.1  1851.2   445.4 1849.04   456.7  1851.3   478.5  1852.4   527.7 1850.94
   541.1 1854.31   556.1 1855.95   580.2 1866.45   644.1 1905.78   688.1 1928.85
#Mann= 7 ,-1 , 0
       0     .06       0  128.67      .1       0  151.44     .06       0
  265.47     .12       0   311.3    .045       0   334.7     .12       0
  516.27      .1       0
#XS Ineff= 2 , 0
                           357.5         1855.58
Permanent Ineff=
       F       F
Bank Sta=311.3,334.7
XS Rating Curve= 0 ,0
Exp/Cntr(USF)=0,0
Exp/Cntr=0.3,0.1

Type RM Length L Ch R = 1 ,14442   ,262.4,268.4,272.4
XS GIS Cut Line= 3
      2489193.12      603704.2842489736.21880311603808.118737342
2489846.35184466603889.946582004
#Sta/Elev= 30
       0 1848.89       7    1845      22 1844.39    58.7 1846.35     132  1846.1
     154 1848.17   205.3 1848.41   237.9 1850.59   241.9 1850.07   254.1 1844.25
   258.2 1843.45   319.3 1844.19   335.6 1845.19     360 1843.09   380.4 1843.42
   388.5 1840.68   392.6 1840.55   404.8  1839.3   421.1 1840.72   429.3 1844.11
   439.9  1845.5   486.3  1845.2   523.3 1846.72   540.4 1846.55   557.6 1848.74
   582.5 1849.95     591 1853.72   616.8 1869.09   655.7 1895.06   690.1 1915.05
#Mann= 6 ,-1 , 0
       0     .06       0   74.65      .1       0   392.6    .045       0
   421.1      .1       0   497.5     .12       0  581.48      .1       0
#XS Ineff= 2 , 0
          378.02 1846.96
Permanent Ineff=
       F       F
Bank Sta=392.6,421.1
XS Rating Curve= 0 ,0
Exp/Cntr=0.3,0.1

Type RM Length L Ch R = 1 ,14174   ,319.6,327.5,330.2
XS GIS Cut Line= 2
     2489154.014      603795.9622489669.04681178604129.067582004
#Sta/Elev= 30
       0  1839.3    48.9 1840.41    69.2 1839.64    92.3 1840.32   110.4 1840.03
   134.3  1841.5   164.6 1841.75   205.7 1844.79   215.2 1843.66   225.4 1837.38
   231.2 1834.98   254.3 1833.96     263 1831.75   280.4 1829.22   285.3 1829.52
   310.5  1833.7   361.3 1832.59   386.7 1833.87   393.2 1833.13   407.6  1831.9
   410.7 1831.96   416.3 1833.42   429.6 1837.79   459.7 1841.57   471.3 1844.09
   484.1 1849.56   503.1 1855.93   550.4 1879.12   579.9 1891.73   613.4 1900.97
#Mann= 9 ,-1 , 0
       0     .06       0   36.27      .1       0  300.19     .12       0
  329.39      .1       0   393.2    .045       0   416.3      .1       0
  434.05     .12       0  475.95      .1       0  567.91     .12       0
#XS Ineff= 2 , 0
          310.77 1840.13
Permanent Ineff=
       F       F
Bank Sta=393.2,416.3
XS Rating Curve= 0 ,0
Exp/Cntr=0.3,0.1

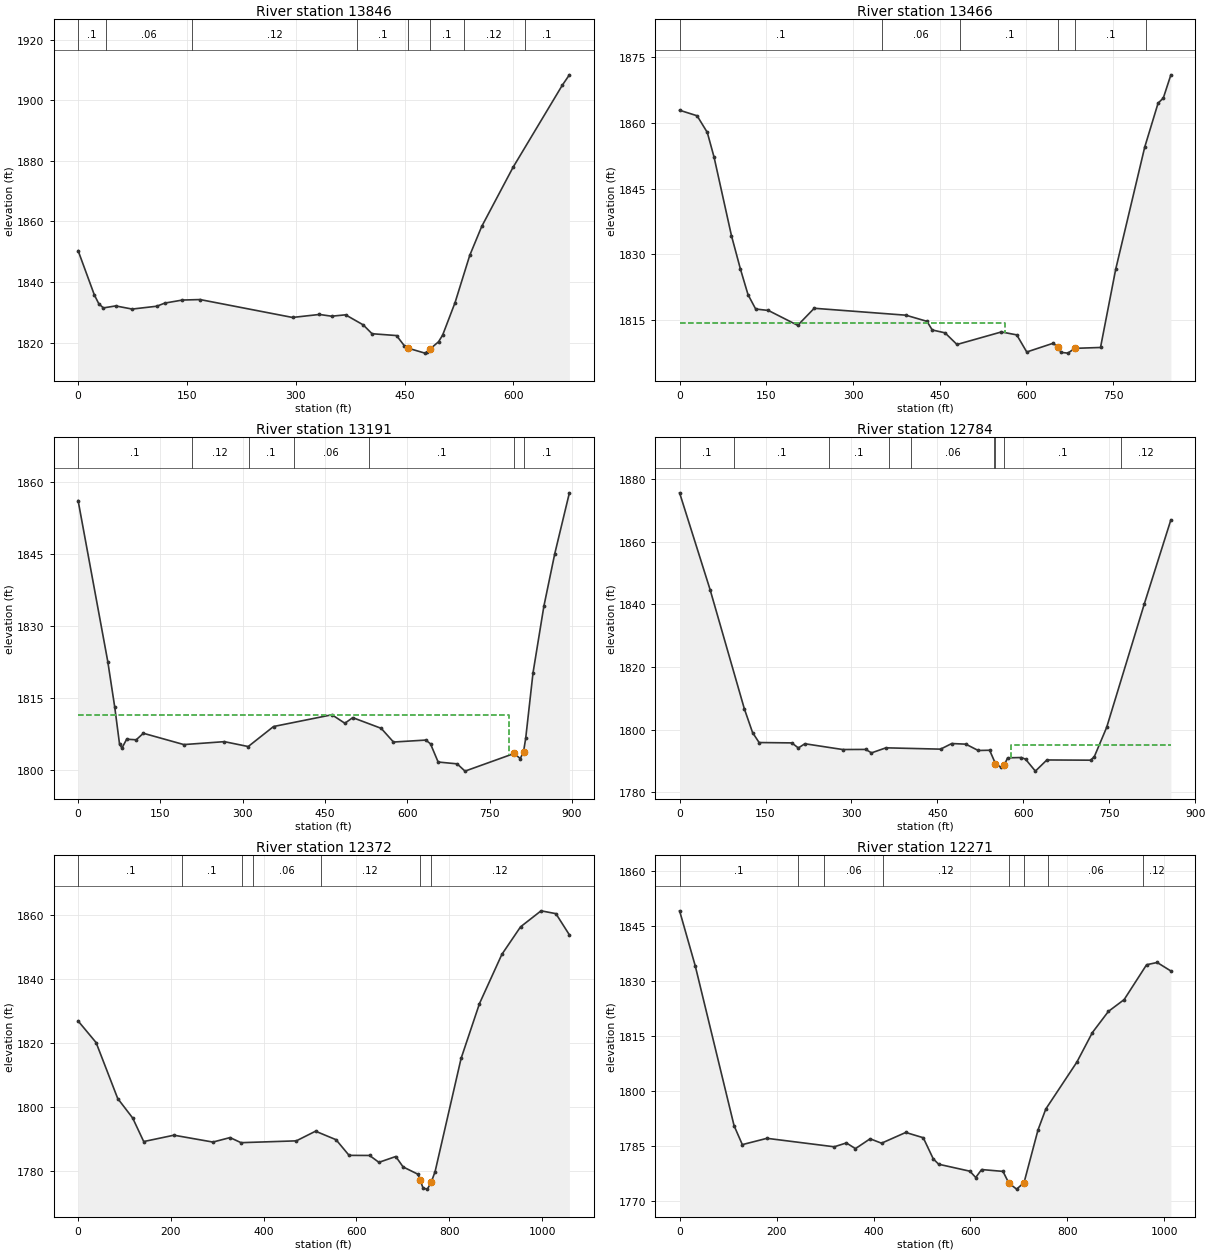
Type RM Length L Ch R = 1 ,13846   ,383.6,380.5,373.7
XS GIS Cut Line= 2
2489011.96364474603908.5206148872489457.91605063604418.234931206
#Sta/Elev= 30
       0 1850.36    22.4 1835.74    28.5 1832.84    34.8 1831.45    51.8 1832.11
    74.5 1831.07   108.5 1832.01   119.6 1833.05   143.9 1834.05   168.1 1834.21
   295.6  1828.3   332.7 1829.29   349.5 1828.71   368.7 1829.17     393 1825.86
   405.2 1822.93     439 1822.32   449.6    1819   454.4 1818.19   478.1 1816.52
   481.5 1816.78   485.6 1817.96   496.9 1820.27   502.6 1822.51   519.6 1833.16
   539.9 1848.79   556.4 1858.34   599.5 1877.83   667.5 1904.98   677.3 1908.42
#Mann= 8 ,-1 , 0
       0      .1       0   38.17     .06       0  156.77     .12       0
  384.55      .1       0   454.4    .045       0   485.6      .1       0
  531.88     .12       0  615.47      .1       0
Bank Sta=454.4,485.6
XS Rating Curve= 0 ,0
Exp/Cntr=0.3,0.1

Type RM Length L Ch R = 1 ,13466   ,270.3,274.9,275.9
XS GIS Cut Line= 3
2488679.20252532604047.386749038 2488843.5412207604403.748987893
2489246.28666249604620.599110347
#Sta/Elev= 30
       0 1862.87    30.3  1861.6    47.9 1857.81    59.6 1852.19    89.7 1834.28
   105.2 1826.66   118.4  1820.8   131.6 1817.53   153.6  1817.2   204.3 1813.81
   232.9  1817.7   391.5 1816.12   427.9 1814.72     437 1812.75   459.1  1812.1
   479.8 1809.44   556.6  1812.3   583.2 1811.63   600.5 1807.73   645.9 1809.71
     655 1808.84   659.6 1807.64   671.7 1807.47   683.6 1808.56   728.1 1808.76
   754.4 1826.62   804.6 1854.47   827.7 1864.49   836.7 1865.64   849.8 1870.94
#Mann= 6 ,-1 , 0
       0      .1       0  349.63     .06       0  485.83      .1       0
     655    .045       0   683.6      .1       0  806.57     .12       0
#XS Ineff= 2 , 0
          562.54 1814.27
Permanent Ineff=
       F       F
Bank Sta=655,683.6
XS Rating Curve= 0 ,0
Exp/Cntr=0.3,0.1

Type RM Length L Ch R = 1 ,13191   ,408.9,406.3,405.2
XS GIS Cut Line= 3
2488393.24933407604321.5386746012488819.25537603604501.793337096
 2489060.6470238604860.905217668
#Sta/Elev= 30
       0  1856.2    54.1  1822.6    66.8 1813.08    75.5  1805.4    79.8 1804.55
    88.5 1806.41   105.9 1806.29   118.9 1807.65   192.7 1805.29   266.6  1805.9
     310 1804.88   356.2 1809.06   462.6 1811.51   486.1 1809.74   500.5 1810.91
   552.3 1808.68   574.7 1805.82   633.7 1806.23   642.2 1805.44   656.1 1801.65
   690.7 1801.27   705.1 1799.75   794.5 1803.43   805.8 1802.37   811.7 1803.78
   815.7 1806.63     829 1820.25   848.8 1834.16   868.7 1845.15   895.3 1857.82
#Mann= 7 ,-1 , 0
       0      .1       0   207.4     .12       0  310.94      .1       0
  392.69     .06       0  529.65      .1       0   794.5    .045       0
   811.7      .1       0
#XS Ineff= 2 , 0
           784.4 1811.38
Permanent Ineff=
       F       F
Bank Sta=794.5,811.7
XS Rating Curve= 0 ,0
Exp/Cntr=0.3,0.1

Type RM Length L Ch R = 1 ,12784   ,392.1,412.5,418.4
XS GIS Cut Line= 2
2488204.38499359604490.6735075872488886.17435969605010.892993587
#Sta/Elev= 30
       0 1875.53    53.2 1844.69   113.1 1806.63   127.4 1799.09   138.8 1795.91
   195.9 1795.79   207.3 1794.18   218.7 1795.52   284.7 1793.68     325 1793.71
     335 1792.61   360.2 1794.22   455.6  1793.8   475.1 1795.59   499.7 1795.39
   521.3 1793.37   541.2 1793.45   551.4 1789.19   561.2 1787.99   566.9 1788.77
   572.6 1791.03   596.7 1791.13     604 1790.58   621.1 1786.79   641.1 1790.35
   717.4 1790.28   723.9 1791.38   745.5 1800.74   811.4 1840.22   857.6 1866.92
#Mann= 9 ,-1 , 0
       0      .1       0   95.01      .1       0  260.04      .1       0
  365.41     .12       0  404.47     .06       0  548.89      .1       0
   551.4    .045       0   566.9      .1       0  771.01     .12       0
#XS Ineff= 2 , 0
                             578         1795.18
Permanent Ineff=
       F       F
Bank Sta=551.4,566.9
XS Rating Curve= 0 ,0
Exp/Cntr=0.3,0.1

Type RM Length L Ch R = 1 ,12372   ,102.2,100.4,106
XS GIS Cut Line= 3
2488133.48742618604622.8820595092488570.86695033604884.979937742
2488620.04169352605431.831573129
#Sta/Elev= 30
       0  1826.9    38.8 1820.14    85.4 1802.64   117.6 1796.55   141.4 1789.18
   206.6 1791.17   290.6 1789.02   327.5 1790.42   351.2 1788.83   470.4  1789.4
   511.8 1792.42     556 1789.76   584.1 1784.86   628.3 1784.83   648.4 1782.68
   684.7  1784.5   700.6 1781.24   732.7 1778.95   737.2 1777.14   743.7 1774.59
   752.8  1774.3   761.2 1776.48   769.5 1779.78   825.5 1815.16   865.2 1832.35
   913.4 1847.72   953.7 1856.34   997.9 1861.35  1029.9 1860.47    1059 1853.83
#Mann= 7 ,-1 , 0
       0      .1       0  224.91      .1       0  353.15     .12       0
  377.42     .06       0  522.73     .12       0   737.2    .045       0
   761.2     .12       0
Bank Sta=737.2,761.2
XS Rating Curve= 0 ,0
Exp/Cntr=0.5,0.3

Type RM Length L Ch R = 1 ,12271   ,81.6,82.4,78.5
XS GIS Cut Line= 4
2488077.75246258604734.7732267482488485.27705366604934.098369979
2488518.03628809605396.1625747322488566.90532544 605479.32467108
#Sta/Elev= 30
       0 1849.21    32.3  1834.2   112.4 1790.59   129.4 1785.43   180.2 1787.15
   318.9 1784.84     344 1785.89   362.7 1784.34     393 1787.02   416.5 1785.82
   466.5 1788.75   502.6 1787.31   523.2 1781.55   534.4 1780.08   598.8 1778.18
   610.8 1776.46   622.9 1778.63     667 1778.13     679 1774.96   695.1 1773.29
   710.4 1775.04   739.2 1789.41   755.3 1795.14   819.4 1807.94   851.4    1816
   884.5 1821.78   916.9 1824.99   963.2  1834.5     985 1835.12  1013.3  1832.8
#Mann= 8 ,-1 , 0
       0      .1       0  243.63      .1       0  298.35     .06       0
     420     .12       0     679    .045       0   710.4     .12       0
  759.55     .06       0  955.91     .12       0
#XS Ineff= 3 ,-1
     500     656    1778     656     667    1775     711     718    1775
Permanent Ineff=
       F       F       F
Bank Sta=679,710.4
XS Rating Curve= 0 ,0
Exp/Cntr=0.5,0.3

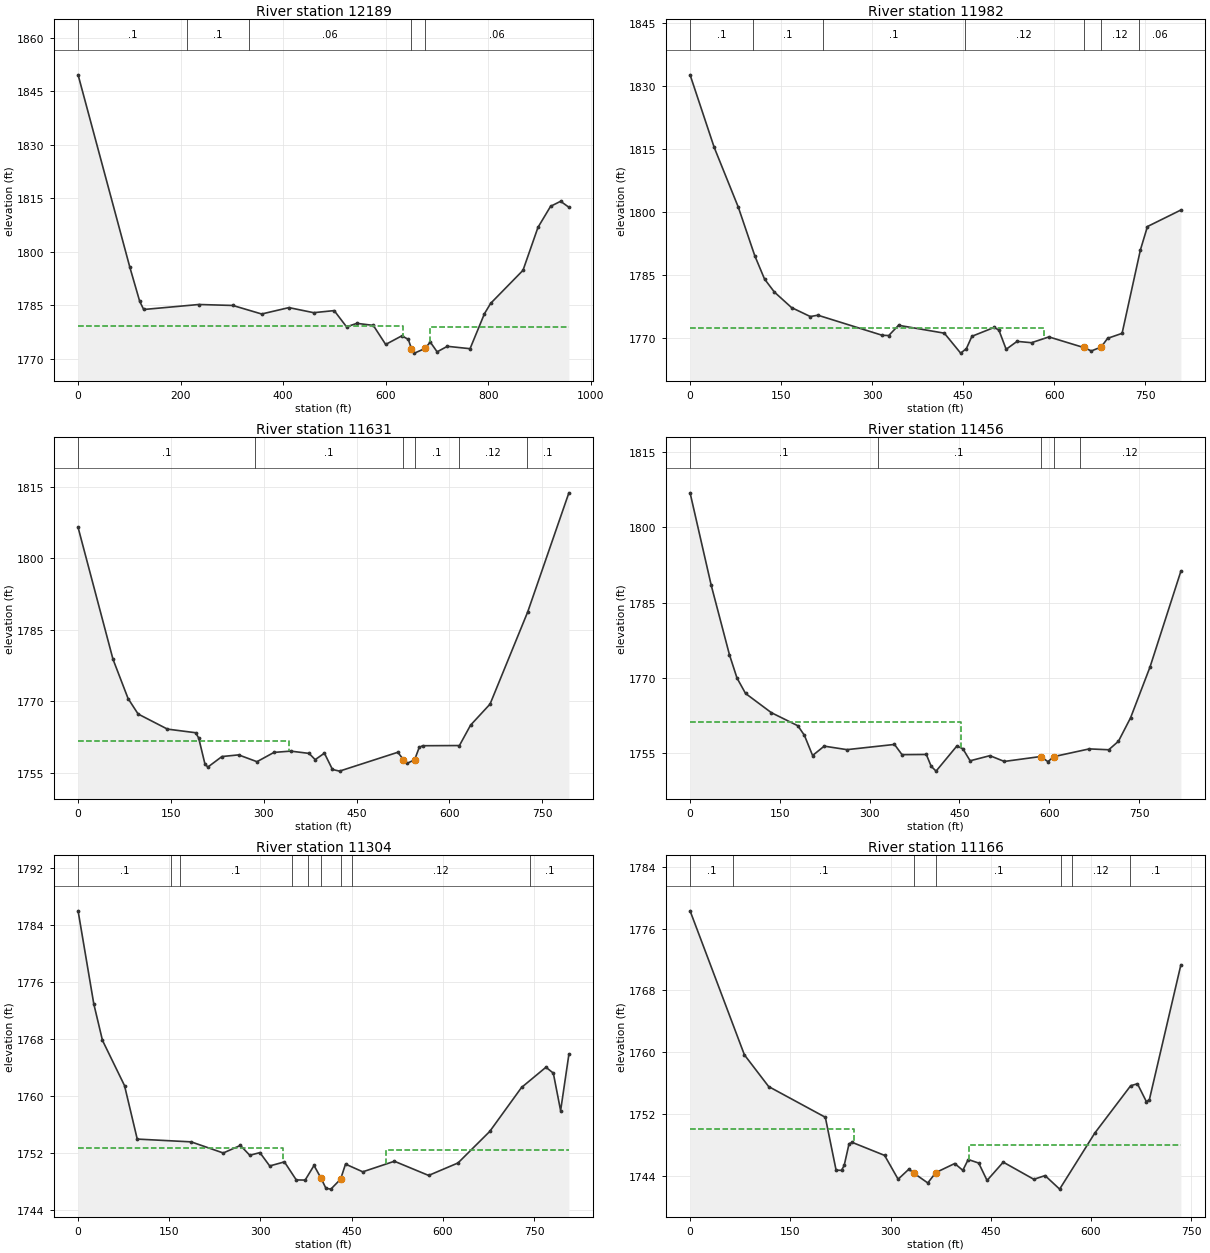
Type RM Length L Ch R = 1 ,12189   ,212.4,207.1,201.3
XS GIS Cut Line= 4
2488054.21206787604776.7596531252488410.93945601604946.860703759
2488447.58276328605371.2666428842488503.48682217605495.429663641
#Sta/Elev= 30
       0 1849.55     101 1795.64   120.2 1786.11     128 1783.82   235.5 1785.22
   301.9 1784.95   358.1 1782.56   411.3 1784.35   459.5 1782.93   499.6 1783.51
   523.7 1778.96   543.8 1779.94   575.9 1779.37     600 1774.03   631.6 1776.45
   644.2 1775.44  650.221772.866   656.2  1771.6   676.7  1772.9     687  1774.7
   700.4 1771.96   720.3 1773.51   764.6 1772.84   792.7 1782.64   804.8 1785.54
   867.9  1794.8   897.1 1806.82   921.7 1812.72   941.3 1814.13   957.4 1812.46
#Mann= 5 ,-1 , 0
       0      .1       0  211.91      .1       0  332.72     .06       0
  650.22    .045       0   676.7     .06       0
#XS Ineff= 2 , 0
          634.37 1779.06  687.33         1778.78
Permanent Ineff=
       F       F
Bank Sta=650.22,676.7
XS Rating Curve= 0 ,0
Exp/Cntr=0.5,0.3

Type RM Length L Ch R = 1 ,11982   ,349.1,351.3,351.7
XS GIS Cut Line= 2
 2487945.6626307604907.7761657562488487.66231964605508.374395671
#Sta/Elev= 30
       0 1832.59    39.8  1815.3    79.6 1801.04   106.6 1789.54   122.7 1783.98
   138.9 1780.88   167.2 1777.18   198.2 1775.04   210.6 1775.36   316.7 1770.58
   327.5 1770.52   343.6 1772.96   419.1 1771.08     446 1766.33   455.4 1767.39
   464.6 1770.34   501.4 1772.46   509.1 1771.79     521 1767.24     539 1769.13
   562.8 1768.81   591.5 1770.19   648.7 1767.67   661.5 1766.85   677.7  1767.8
   688.2 1769.85   712.1 1771.04   742.3 1790.91   753.9 1796.47     809  1800.4
#Mann= 7 ,-1 , 0
       0      .1       0  103.06      .1       0  219.67      .1       0
  452.89     .12       0   648.7    .045       0   677.7     .12       0
  740.35     .06       0
#XS Ineff= 2 , 0
           583.6 1772.22
Permanent Ineff=
       F       F
Bank Sta=648.7,677.7
XS Rating Curve= 0 ,0
Exp/Cntr=0.3,0.1

Type RM Length L Ch R = 1 ,11631   ,167.2,174.9,177.7
XS GIS Cut Line= 2
2487789.41028949605157.6738775462488258.02022675605797.656319346
#Sta/Elev= 30
       0 1806.48    56.4 1778.82    80.8 1770.57      97 1767.32   144.4 1764.15
   189.9 1763.39   194.9 1762.29     205 1756.84   209.7 1756.18   232.5 1758.39
   259.4 1758.74   289.1 1757.31   316.6 1759.26   343.6 1759.53   373.3 1759.05
   383.2 1757.74   398.1  1759.1   411.1 1755.68   422.5 1755.33   516.8 1759.29
   525.6 1757.76     532 1756.98   543.9 1757.71   551.3  1760.3   556.8 1760.66
   616.3  1760.7   634.3 1764.98   665.8  1769.4   726.7 1788.76   793.2 1813.74
#Mann= 6 ,-1 , 0
       0      .1       0  285.34      .1       0   525.6    .045       0
   543.9      .1       0  614.87     .12       0  724.72      .1       0
#XS Ineff= 2 , 0
          341.26  1761.6
Permanent Ineff=
       F       F
Bank Sta=525.6,543.9
XS Rating Curve= 0 ,0
Exp/Cntr=0.3,0.1

Type RM Length L Ch R = 1 ,11456   ,151.6,152.1,147
XS GIS Cut Line= 3
2487756.89100012  605191.53803342487954.72375176605472.947188135
2488038.30015486605941.609802975
#Sta/Elev= 30
       0 1806.86    35.3 1788.45    65.8 1774.59    78.4 1769.95    92.7 1766.88
   135.8 1763.05   180.1 1760.44     191 1758.54   204.7 1754.51   224.1 1756.38
   262.1 1755.68   341.5 1756.72   354.1 1754.68   394.7 1754.72   402.8 1752.37
     411  1751.4   445.7  1756.4   455.7 1755.87   467.9 1753.46   500.9 1754.48
     525 1753.33   585.7 1754.31   597.9 1753.29   607.7 1754.29   666.9 1755.83
   699.5 1755.66   715.7 1757.35     736 1762.04   768.5 1772.17     820 1791.24
#Mann= 5 ,-1 , 0
       0      .1       0  313.26      .1       0   585.7    .045       0
   607.7      .1       0  650.65     .12       0
#XS Ineff= 2 , 0
          452.23 1761.12
Permanent Ineff=
       F       F
Bank Sta=585.7,607.7
XS Rating Curve= 0 ,0
Exp/Cntr(USF)=0,0
Exp/Cntr=0.3,0.1

Type RM Length L Ch R = 1 ,11304   ,133.6,138.1,133.1
XS GIS Cut Line= 3
2487724.82487755605292.273707485 2487845.7615664605436.744882167
2487909.26756054606052.327219043
#Sta/Elev= 30
       0 1785.98    25.9  1772.9    40.1 1767.81    76.4 1761.46    97.3 1753.96
     186 1753.57   238.8 1752.01     267 1753.07   282.4 1751.69   299.1 1752.06
   315.2 1750.19   339.4 1750.76   358.9 1748.23   373.5 1748.21   388.1 1750.26
   399.7 1748.46   407.7 1747.05   415.8 1746.94   431.8 1748.34   439.9 1750.45
   468.3 1749.37   520.3 1750.85   576.6 1748.86   624.9 1750.61   677.1 1755.03
   729.4  1761.2   769.6 1764.04   781.7 1763.21   793.7 1757.95   807.3 1765.84
#Mann= 9 ,-1 , 0
       0      .1       0  152.14      .1       0  166.93      .1       0
  352.64      .1       0  377.91      .1       0   399.7    .045       0
   431.8      .1       0   450.3     .12       0  743.28      .1       0
#XS Ineff= 2 , 0
           336.8 1752.66  506.23         1752.36
Permanent Ineff=
       F       F
Bank Sta=399.7,431.8
XS Rating Curve= 0 ,0
Exp/Cntr=0.3,0.1

Type RM Length L Ch R = 1 ,11166   ,169.1,168.9,167.1
XS GIS Cut Line= 3
2487707.05344951605362.2463230592487768.71273734605832.445683681
2487885.46558503606064.997319346
#Sta/Elev= 30
       0 1778.29    81.3 1759.67   117.6 1755.57   202.4  1751.6   218.5 1744.76
   226.6 1744.74   230.6 1745.37   237.9 1748.18   242.7 1748.35   291.1 1746.67
   311.3 1743.59   327.4 1744.89   335.4 1744.34   355.7 1743.11   367.7 1744.45
     396 1745.62   408.1 1744.74   416.2 1746.14   431.9 1745.68   444.4 1743.43
   468.6  1745.8   514.4 1743.58   531.2 1744.06     553 1742.31   605.7 1749.57
   659.3 1755.68   669.4 1755.93   682.8 1753.62   687.3 1753.89   734.4 1771.31
#Mann= 7 ,-1 , 0
       0      .1       0   63.87      .1       0   335.4    .045       0
   367.7      .1       0  555.55      .1       0  571.26     .12       0
     658      .1       0
#XS Ineff= 2 , 0
          245.78 1750.12  417.63         1747.98
Permanent Ineff=
       F       F
Bank Sta=335.4,367.7
XS Rating Curve= 0 ,0
Exp/Cntr=0.3,0.1

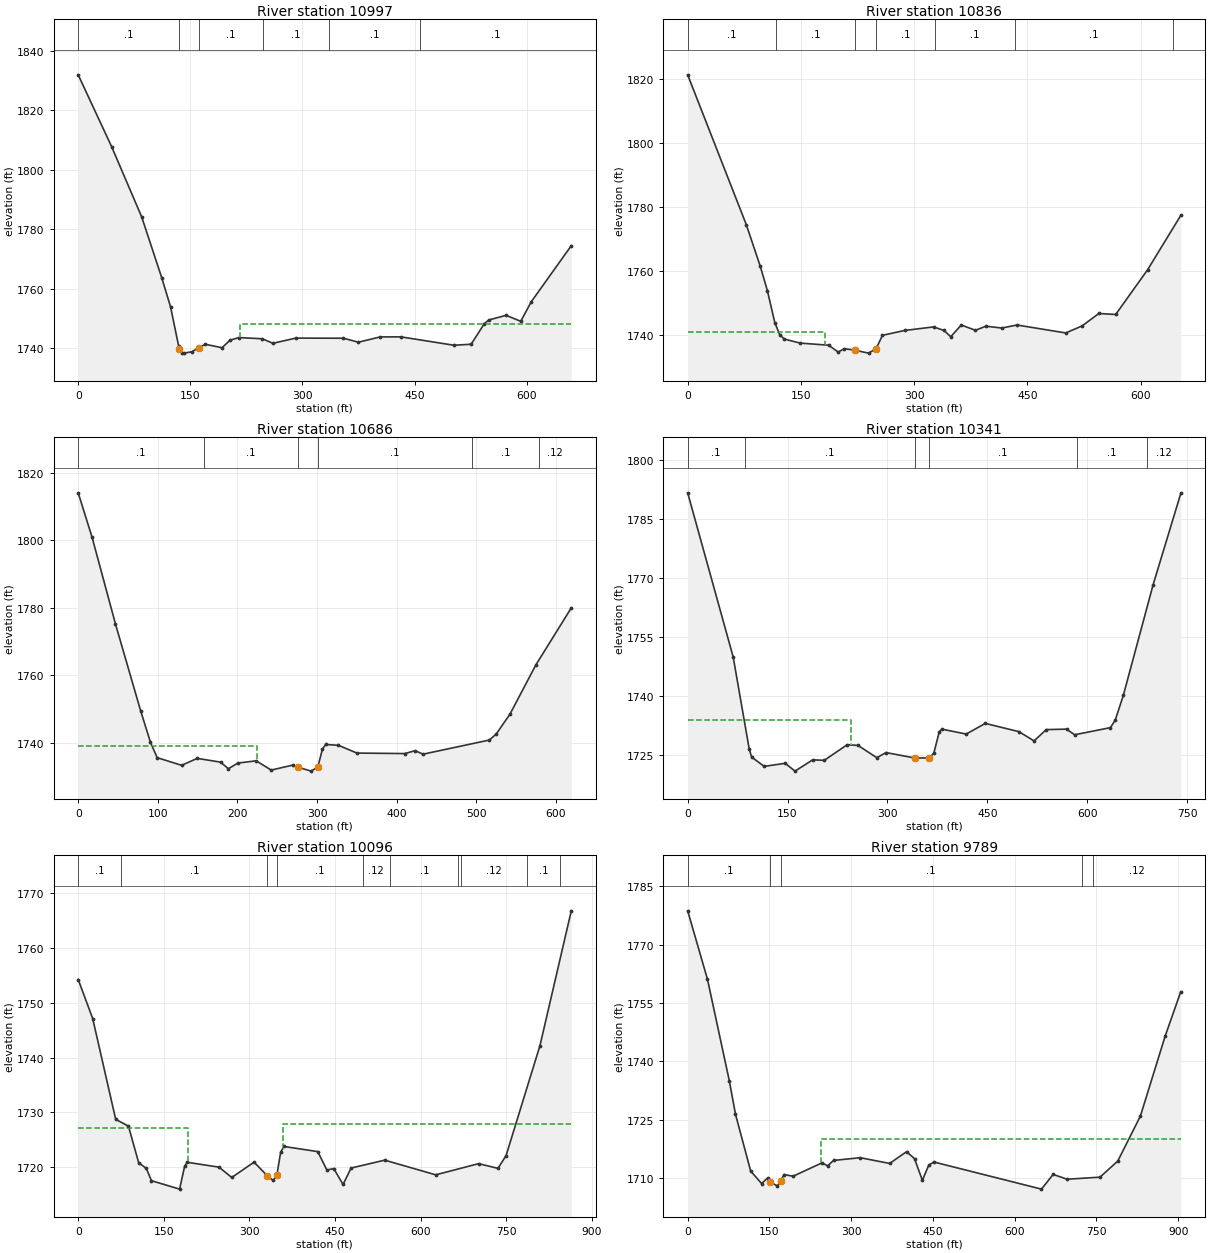
Type RM Length L Ch R = 1 ,10997   ,171.8,160.4,153.3
XS GIS Cut Line= 3
2487540.64841336605511.0033316032487680.36049122605787.862698482
2487865.80246371606084.217024369
#Sta/Elev= 30
       0 1831.86    44.7 1807.72    84.9 1784.12   111.7  1763.7   123.6 1753.83
   134.3 1740.77   135.5 1739.85   138.5 1738.43   141.4  1738.3   152.2 1738.76
   161.2 1740.13   170.1 1741.27   192.5 1740.12     203 1742.63   214.9 1743.53
   246.3 1743.13   260.5  1741.6   291.1 1743.35   354.7 1743.31     375 1741.97
     404 1743.75   431.7 1743.77   502.7 1740.95   525.7 1741.29   543.3 1748.17
   549.1 1749.42   572.4 1751.01   592.1    1749   606.2 1755.58   659.7 1774.42
#Mann= 6 ,-1 , 0
       0      .1       0   135.5    .045       0   161.2      .1       0
     247      .1       0  335.53      .1       0  457.03      .1       0
#XS Ineff= 2 , 0
                          216.69         1747.93
Permanent Ineff=
       F       F
Bank Sta=135.5,161.2
XS Rating Curve= 0 ,0
Exp/Cntr=0.3,0.1

Type RM Length L Ch R = 1 ,10836   ,143.9,150.3,151.7
XS GIS Cut Line= 3
2487372.66444015605724.3524030682487681.59920783605821.788390479
 2487849.1496704606105.114670405
#Sta/Elev= 30
       0 1821.38    77.7 1774.48    96.2 1761.45   105.7 1753.75   115.4 1743.87
   121.8 1740.14     128 1738.72     149 1737.46   186.7  1736.8   199.3 1734.66
   207.7 1735.73   221.2 1735.24   239.6 1734.32   249.6 1735.69     258 1739.89
   287.4 1741.41   325.6 1742.52   339.2 1741.45   348.5 1739.46   362.4 1743.11
   381.2 1741.46   394.9 1742.74   416.1 1742.17   436.2 1743.12   500.8 1740.63
   522.6 1742.86   544.6 1746.72   566.9 1746.41   609.1 1760.37   653.1 1777.39
#Mann= 7 ,-1 , 0
       0      .1       0  117.32      .1       0   221.2    .045       0
   249.6      .1       0  328.01      .1       0  433.03      .1       0
  643.08     .12       0
#XS Ineff= 2 , 0
          181.88 1740.81
Permanent Ineff=
       F       F
Bank Sta=221.2,249.6
XS Rating Curve= 0 ,0
Exp/Cntr=0.3,0.1

Type RM Length L Ch R = 1 ,10686   ,343.1,344.6,336.9
XS GIS Cut Line= 2
2487328.43315953605769.8281714362487835.12118265606125.949072785
#Sta/Elev= 30
       0 1814.03    17.5 1800.81    46.8 1775.18    78.4 1749.49    90.8 1740.09
    99.2 1735.57   129.9  1733.3   149.5 1735.36   178.8 1734.24   188.6 1732.29
   200.5 1733.96   223.5 1734.64   242.4 1731.89   269.4 1733.36   276.6 1732.72
   292.4 1731.58     301 1732.79     301 1732.81   306.8 1738.15   310.8 1739.47
   326.9 1739.23     350 1736.93   410.1 1736.78   423.3 1737.64   433.1  1736.6
   516.4 1740.79     525 1742.56   542.2 1748.43   574.9 1763.08   619.3 1779.94
#Mann= 6 ,-1 , 0
       0      .1       0  157.57      .1       0   276.6    .045       0
     301      .1       0  495.22      .1       0  579.34     .12       0
#XS Ineff= 2 , 0
          225.02 1739.11
Permanent Ineff=
       F       F
Bank Sta=276.6,301
XS Rating Curve= 0 ,0
Exp/Cntr=0.3,0.1

Type RM Length L Ch R = 1 ,10341   ,237.2,245.1,251.2
XS GIS Cut Line= 3
 2487199.0836228605917.0747445642487305.93640169 606121.55421973
2487807.55482925606212.980987411
#Sta/Elev= 30
       0 1791.63    68.4 1749.92    92.3 1726.72      96 1724.56   114.9 1722.19
   146.5 1722.96   161.2 1720.98   187.8 1723.85   205.1 1723.72   239.7 1727.69
   255.9  1727.5   284.1 1724.39   297.9 1725.69   341.3 1724.31   363.2 1724.33
   369.8 1725.59   377.9 1730.99     382 1731.63   418.3 1730.39     447 1733.09
   497.4 1731.01   520.2 1728.66   538.6 1731.52     569 1731.64   581.2 1730.21
   634.9 1732.02   642.2 1733.94   654.4 1740.25   699.1 1768.31   740.6 1791.46
#Mann= 6 ,-1 , 0
       0      .1       0   85.74      .1       0   341.3    .045       0
   363.2      .1       0  584.64      .1       0  690.03     .12       0
#XS Ineff= 2 , 0
           244.7 1733.85
Permanent Ineff=
       F       F
Bank Sta=341.3,363.2
XS Rating Curve= 0 ,0
Exp/Cntr=0.3,0.1

Type RM Length L Ch R = 1 ,10096   ,301.7,307.4,301.5
XS GIS Cut Line= 3
2487101.84794634606024.2364508792487208.65922825606236.091053233
2487646.32718217606685.031182168
#Sta/Elev= 30
       0 1754.25    25.4 1747.13    65.7 1728.73    88.1 1727.47     106  1720.8
   119.4 1719.75   128.4 1717.52   177.7 1715.98   186.6 1720.18   191.1 1720.88
   246.8 1719.99   269.1 1718.11   308.2  1720.9   331.2 1718.45   341.7 1717.56
   348.2 1718.54   354.8  1722.7   360.6 1723.77   419.9 1722.83   435.9 1719.46
   447.9 1719.74   464.2 1716.83   478.3 1719.83   537.2 1721.27   626.6 1718.59
   701.8 1720.63   735.7 1719.77   749.9  1722.1   809.3 1742.18   864.2 1766.79
#Mann= 10 ,-1 , 0
       0      .1       0   75.79      .1       0   331.2    .045       0
   348.2      .1       0  498.29     .12       0  546.76      .1       0
  666.48      .1       0  671.17     .12       0   786.2      .1       0
  844.06     .12       0
#XS Ineff= 2 , 0
          191.94 1727.11  358.46         1727.84
Permanent Ineff=
       F       F
Bank Sta=331.2,348.2
XS Rating Curve= 0 ,0
Exp/Cntr=0.3,0.1

Type RM Length L Ch R = 1 ,9789    ,290.1,288.6,280.6
XS GIS Cut Line= 2
2486909.40645612606169.4588957062487452.06247771606893.453922536
#Sta/Elev= 30
       0 1778.64    36.3 1761.09    76.3  1735.1    87.7 1726.48   115.6 1711.89
   135.6 1708.69   146.8  1710.1   150.6 1709.11   164.8 1708.06   170.6 1709.31
   176.8 1710.99   193.4 1710.56   246.7    1714   256.7 1713.21   267.7 1714.61
   316.7 1715.31   370.6 1713.84   401.7 1716.86   416.3 1715.06   430.6 1709.52
   442.4 1713.39   451.7 1714.21   649.2 1707.25   670.6 1711.02   696.3 1709.79
   756.6 1710.32   789.2 1714.45   830.6 1725.94   876.3 1746.55   904.8 1757.89
#Mann= 5 ,-1 , 0
       0      .1       0   150.6    .045       0   170.6      .1       0
  722.83      .1       0  743.71     .12       0
#XS Ineff= 2 , 0
                          244.52          1720.2
Permanent Ineff=
       F       F
Bank Sta=150.6,170.6
XS Rating Curve= 0 ,0
Exp/Cntr=0.3,0.1