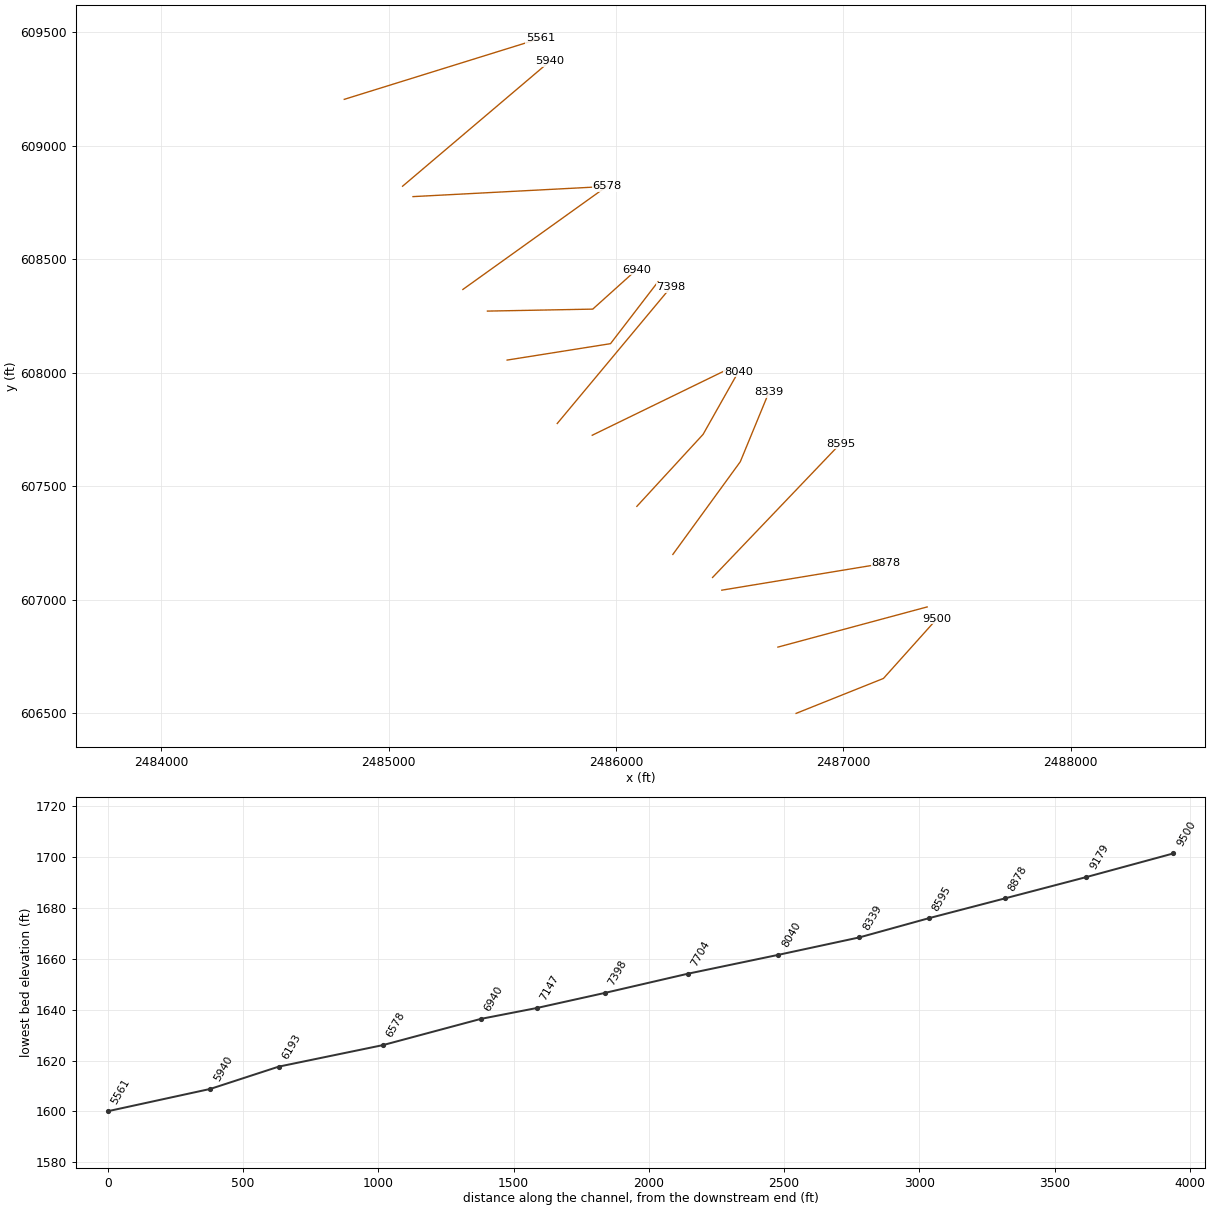
HEC-RAS study STONYRN1.prj: STONYRN1

--- STONYRN1.g01 (geometry) --- (continued)

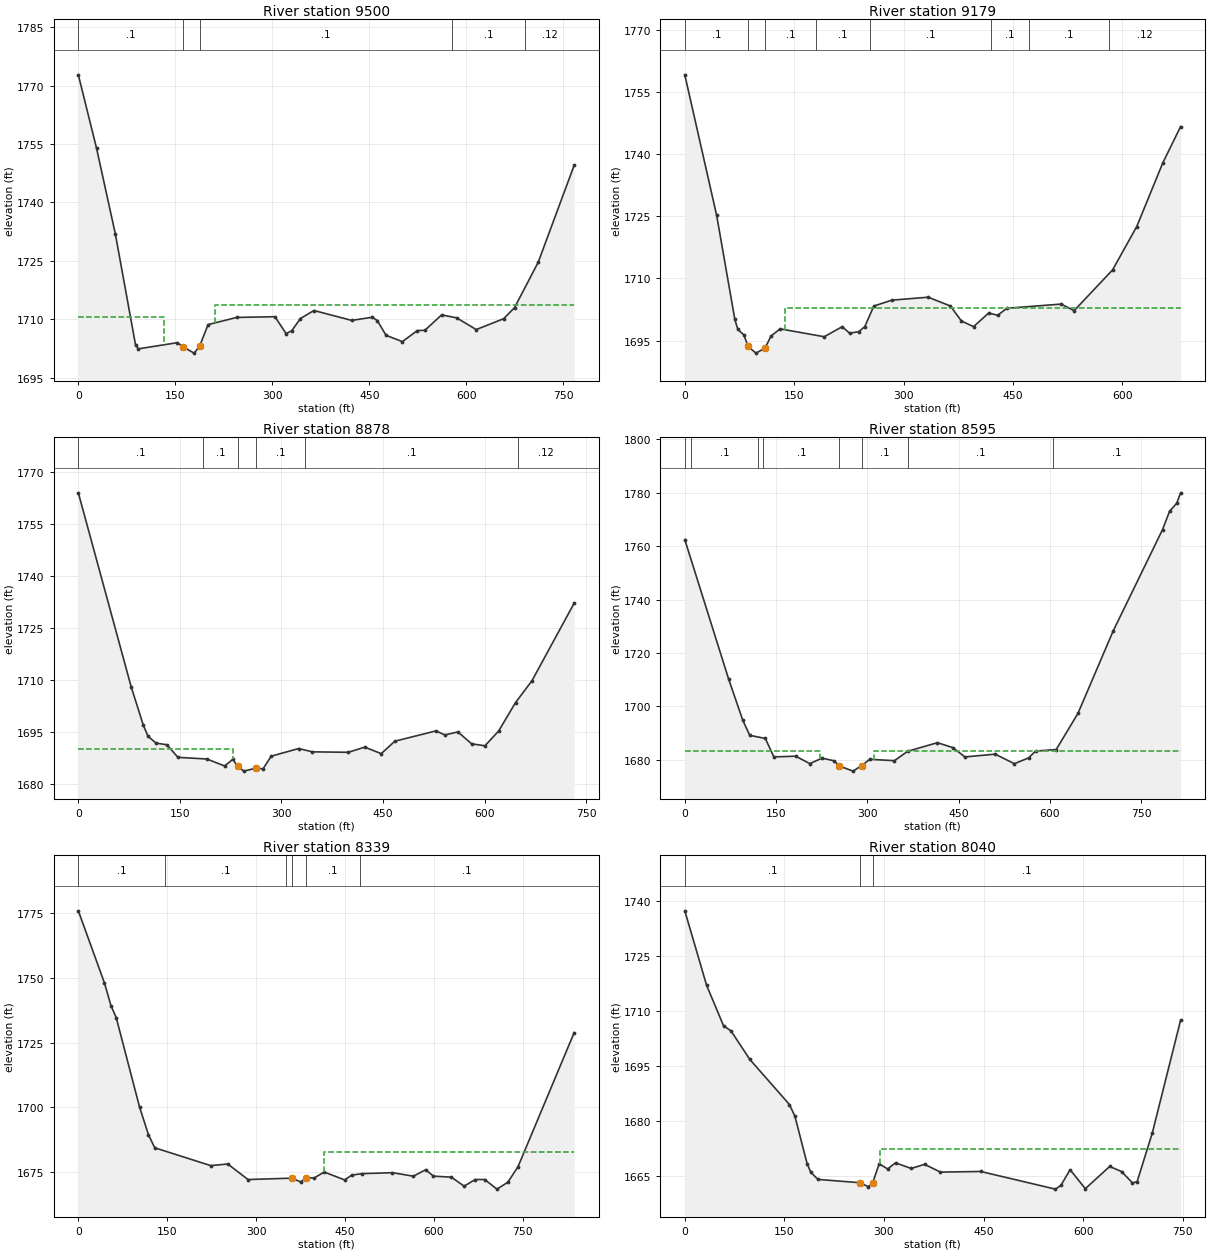
Type RM Length L Ch R = 1 ,9500    ,320.2,321.5,317.8
XS GIS Cut Line= 3
2486792.59027053 606498.573477712487176.56179786606652.572907203
2487411.76557555606915.637341741
#Sta/Elev= 30
       0 1772.77    28.2 1753.87    57.3 1731.84    88.5 1703.34    92.8 1702.37
   153.2 1703.96   161.6  1702.9     179 1701.27   187.6 1703.09   200.6  1708.6
   244.9 1710.44     304 1710.63   321.2 1706.29   329.9 1707.01   343.3 1710.15
   364.3 1712.22   422.6 1709.68   454.4 1710.48   462.2 1709.65   475.8 1705.84
     501 1704.23   524.1 1707.06   535.9 1707.14   561.7  1711.1     585 1710.33
   615.2 1707.32   657.7 1710.12   674.4 1712.95     711 1724.61   766.6 1749.53
#Mann= 5 ,-1 , 0
       0      .1       0   161.6    .045       0   187.6      .1       0
  578.33      .1       0  690.28     .12       0
#XS Ineff= 2 , 0
          131.81 1710.59  212.03         1713.76
Permanent Ineff=
       F       F
Bank Sta=161.6,187.6
XS Rating Curve= 0 ,0
Exp/Cntr=0.3,0.1

Type RM Length L Ch R = 1 ,9179    ,300.8,301.1,295.4
XS GIS Cut Line= 2
2486712.53690075606790.6972604412487368.89691225606967.827119427
#Sta/Elev= 30
       0 1759.08    43.7 1725.18    68.6 1700.14    72.7 1697.72      81  1696.4
    86.8  1693.6    97.6    1692     110 1693.21   118.3 1696.13   130.7 1697.85
   191.2 1695.95   215.7 1698.36     226 1696.82   238.4 1697.16   246.7 1698.37
   259.2 1703.35     284 1704.77   333.7 1705.48   364.1 1703.36   379.3 1699.75
   395.9 1698.38   416.6 1701.66     429 1701.12   441.5 1702.81     516 1703.82
   533.8 1702.24   586.5 1712.06   619.6 1722.49   655.4 1737.87   679.8 1746.62
#Mann= 8 ,-1 , 0
       0      .1       0    86.8    .045       0     110      .1       0
  179.53      .1       0  254.42      .1       0     420      .1       0
  472.39      .1       0  581.37     .12       0
#XS Ineff= 2 , 0
                          137.29         1702.93
Permanent Ineff=
       F       F
Bank Sta=86.8,110
XS Rating Curve= 0 ,0
Exp/Cntr=0.3,0.1

Type RM Length L Ch R = 1 ,8878    ,270.7,282.8,291.3
XS GIS Cut Line= 2
2486465.64177091607041.6716124522487188.18317914607161.052255397
#Sta/Elev= 30
       0 1764.02    78.1 1707.94      96 1696.89   102.9 1693.71   114.6 1691.74
   130.9 1691.24   147.1 1687.61   189.9 1687.13     216 1685.13   228.2 1687.03
   235.1 1685.08   244.4 1683.63   262.1 1684.48   272.8  1684.3   284.9 1687.95
   325.5 1690.16   345.7  1689.2   398.7 1689.07     423 1690.56   447.4 1688.68
   467.4 1692.27   528.2 1695.25   541.3 1694.08   560.6 1694.95   580.9 1691.52
   600.5 1690.95   620.9 1695.25   645.7 1703.43   670.1 1709.78   732.3 1732.15
#Mann= 6 ,-1 , 0
       0      .1       0  184.85      .1       0   235.1    .045       0
   262.1      .1       0  334.57      .1       0  648.92     .12       0
#XS Ineff= 2 , 0
          228.27    1690
Permanent Ineff=
       F       F
Bank Sta=235.1,262.1
XS Rating Curve= 0 ,0
Exp/Cntr=0.3,0.1

Type RM Length L Ch R = 1 ,8595    ,256.4,255.3,256.2
XS GIS Cut Line= 2
2486424.99304822607097.6657877762486987.24300504607687.545064758
#Sta/Elev= 30
       0 1762.43    72.1 1710.22    95.3 1694.84   106.8 1689.19   132.3 1688.05
   146.4 1681.13   182.3  1681.4   205.5 1678.61   225.6 1680.68   245.4 1679.67
   253.9 1677.74   276.5 1675.81   290.7 1677.87     304 1680.23   344.6 1679.72
   366.4 1683.25   415.2 1686.45   440.6 1684.61   460.4 1681.12   510.1 1682.16
   541.7 1678.59   564.9 1680.75   576.5 1683.31   610.4 1683.89   646.1 1697.39
     704 1728.23   785.2  1766.2   796.8 1773.07   808.4 1776.02   814.9 1779.95
#Mann= 8 ,-1 , 0
       0      .1       0   10.55      .1       0  120.75      .1       0
  129.33      .1       0   253.9    .045       0   290.7      .1       0
  366.88      .1       0  604.43      .1       0
#XS Ineff= 2 , 0
          222.44 1683.39  310.18          1683.5
Permanent Ineff=
       F       F
Bank Sta=253.9,290.7
XS Rating Curve= 0 ,0
Exp/Cntr=0.3,0.1

Type RM Length L Ch R = 1 ,8339    ,298.9,299.4,298.5
XS GIS Cut Line= 3
2486250.36057051607199.1989669172486546.92492879607607.769515837
2486673.01210289607914.522021586
#Sta/Elev= 30
       0 1776.02    44.1 1748.09    55.1  1739.3    63.9 1734.71   103.2 1700.16
   118.2 1689.43   128.9 1684.31   223.4 1677.42   252.1 1678.04   286.3 1672.03
   360.4 1672.57   375.3 1671.07   383.8 1672.67   398.1 1672.68   414.8 1674.93
   449.4 1671.88   461.1 1673.74   479.1 1674.31   529.9 1674.68   565.3 1673.33
   586.1 1675.83   599.1 1673.34   629.3 1672.95   650.9 1669.47   669.6 1672.04
   685.5 1672.04   706.3 1668.32   724.7    1671   741.8 1677.01   836.5 1728.88
#Mann= 6 ,-1 , 0
       0      .1       0  146.31      .1       0  349.88      .1       0
   360.4    .045       0   383.8      .1       0  475.13      .1       0
#XS Ineff= 2 , 0
                          415.04         1682.78
Permanent Ineff=
       F       F
Bank Sta=360.4,383.8
XS Rating Curve= 0 ,0
Exp/Cntr=0.3,0.1

Type RM Length L Ch R = 1 ,8040    ,337.1,335.8,330.3
XS GIS Cut Line= 3
2486092.10118419607411.1653417412486383.40676587607728.575772234
2486538.41437482608004.059885617
#Sta/Elev= 30
       0 1737.34    32.8 1717.07    58.3 1706.04    69.6 1704.61    97.9 1696.85
   157.7 1684.53   165.9 1681.33   184.2 1668.45   189.7 1666.11   200.5 1664.13
   264.2 1663.22   276.3 1662.13  282.781663.091   292.8 1668.38   305.6 1666.98
   317.4 1668.65   341.1 1667.11   361.2 1668.24   385.1 1666.12   445.8 1666.29
   558.3 1661.48   566.6  1662.5   580.4 1666.78   603.3  1661.6     640 1667.65
   657.9 1666.28   674.2 1663.21   681.3 1663.47   704.3 1676.83   746.9 1707.56
#Mann= 3 ,-1 , 0
       0      .1       0   264.2    .045       0  282.78      .1       0
#XS Ineff= 2 , 0
                          294.09         1672.41
Permanent Ineff=
       F       F
Bank Sta=264.2,282.78
XS Rating Curve= 0 ,0
Exp/Cntr=0.3,0.1

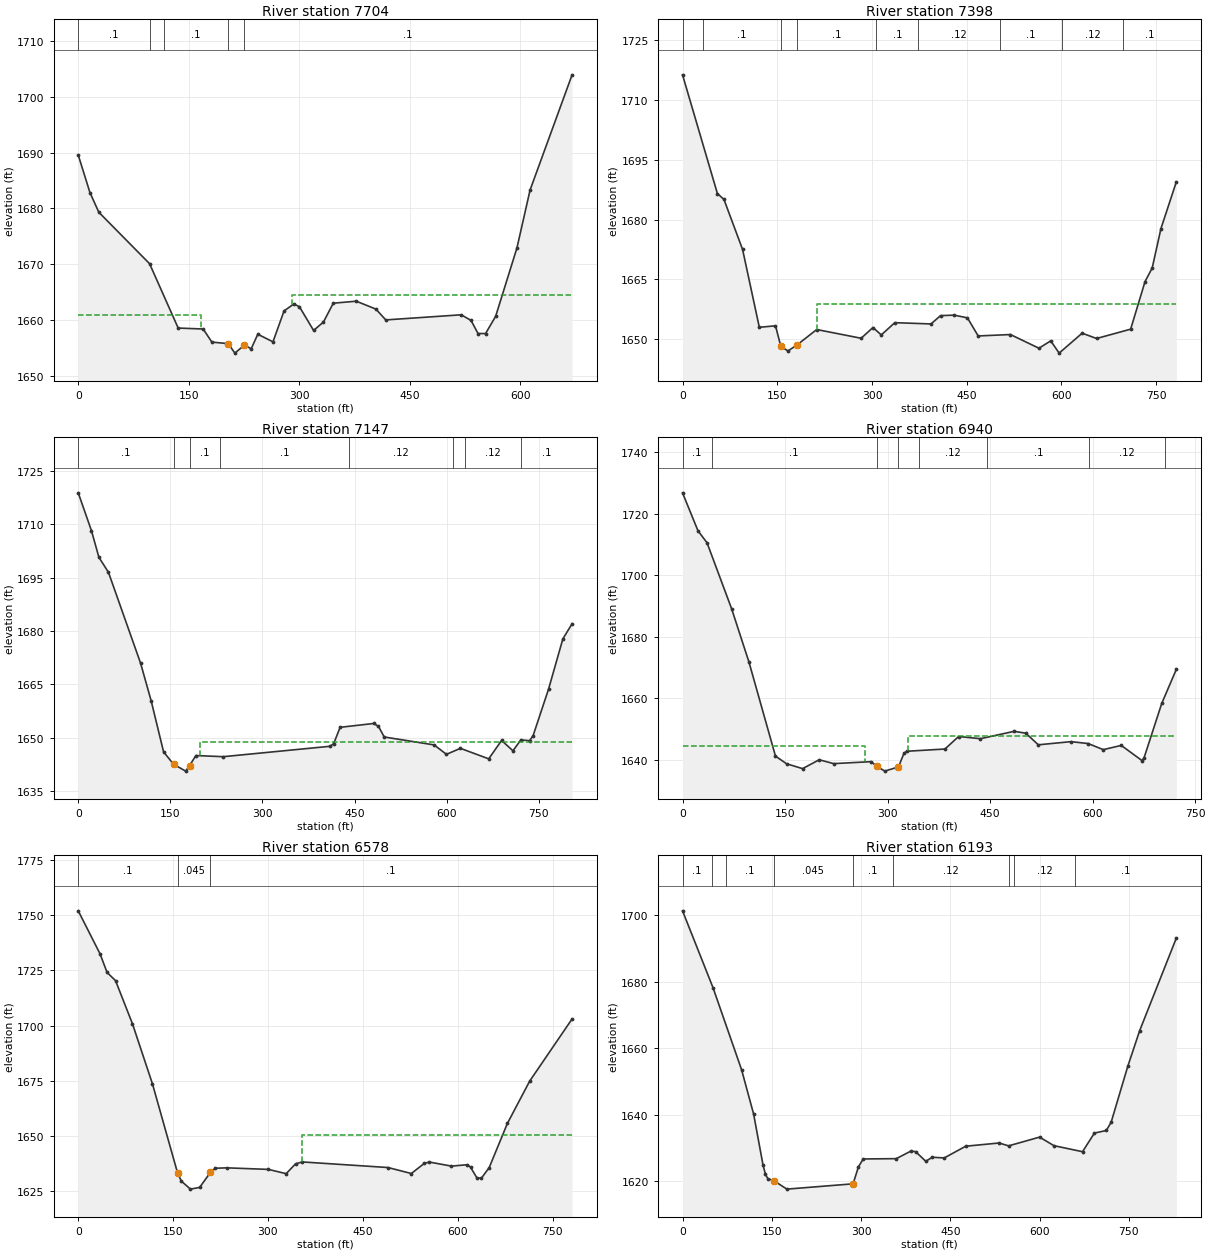
Type RM Length L Ch R = 1 ,7704    ,302.5,305.9,308
XS GIS Cut Line= 2
2485895.76501775607724.5937879752486497.97879706608018.370029857
#Sta/Elev= 30
       0  1689.6    15.9 1682.85    27.9 1679.33    96.8 1670.09   135.6 1658.54
   169.5 1658.37   181.3 1656.02   203.6 1655.74   212.5 1654.04   225.3 1655.47
   234.7 1654.83   243.6 1657.43   264.2 1656.07   279.3 1661.63   292.6 1662.86
   300.1 1662.37   319.3 1658.11   332.7 1659.62     346    1663   377.2 1663.36
   403.9 1661.94   417.2    1660   519.6 1660.92   532.9 1659.91   542.4 1657.56
   552.6 1657.55   566.3 1660.64   595.2 1672.92     613 1683.31     670 1703.99
#Mann= 5 ,-1 , 0
       0      .1       0   97.26      .1       0   116.4      .1       0
   203.6    .045       0   225.3      .1       0
#XS Ineff= 2 , 0
          166.33 1660.96  289.87         1664.52
Permanent Ineff=
       F       F
Bank Sta=203.6,225.3
XS Rating Curve= 0 ,0
Exp/Cntr=0.3,0.1

Type RM Length L Ch R = 1 ,7398    ,262.7,251,244.4
XS GIS Cut Line= 2
 2485741.9325344607776.4628957062486241.89241497608377.615623967
#Sta/Elev= 30
       0 1716.33    55.2 1686.56    65.6 1685.07    95.1 1672.53   121.6 1653.01
   147.2 1653.38   155.7  1648.2     167 1647.08   181.2 1648.57   212.5 1652.45
   282.8 1650.26   301.5 1652.95   314.7  1651.1   336.1 1654.17   393.4 1653.85
   408.5 1655.93   429.8 1656.06   451.1 1655.38   468.1 1650.84   519.2 1651.19
   564.3 1647.76     583 1649.61   596.3 1646.53   632.7 1651.53   655.6  1650.2
   709.5 1652.54   732.3 1664.48   743.6 1667.87   757.5 1677.78   781.9 1689.51
#Mann= 9 ,-1 , 0
       0      .1       0   32.52      .1       0   155.7    .045       0
   181.2      .1       0  306.87      .1       0   373.6     .12       0
  502.32      .1       0  600.99     .12       0  697.77      .1       0
#XS Ineff= 2 , 0
                          213.15          1658.9
Permanent Ineff=
       F       F
Bank Sta=155.7,181.2
XS Rating Curve= 0 ,0
Exp/Cntr=0.3,0.1

Type RM Length L Ch R = 1 ,7147    ,210.3,207.4,208.9
XS GIS Cut Line= 3
2485521.46651362608055.9054119432485976.18840025608128.242382086
 2486185.3147672 608401.30906274
#Sta/Elev= 30
       0 1718.88    21.5 1708.25    33.7 1700.74    49.2 1696.54   101.6 1670.95
   118.8 1660.38     139 1646.04   155.2 1642.56     175 1640.62   181.31642.174
   191.7    1645   236.2 1644.68   410.4 1647.61   416.1 1648.37   426.6 1652.94
   481.3 1654.02     489 1653.22   498.4 1650.22   579.7 1647.99   599.8 1645.34
   622.5 1647.03   668.6 1644.08   689.6 1649.24   708.1 1646.34   720.9  1649.4
   735.2 1649.18   740.9 1650.59   766.1 1663.69   789.4 1677.81   804.4 1682.06
#Mann= 8 ,-1 , 0
       0      .1       0   155.2    .045       0   181.3      .1       0
  231.28      .1       0  440.43     .12       0  610.82      .1       0
  630.18     .12       0  721.93      .1       0
#XS Ineff= 2 , 0
                          197.97         1648.73
Permanent Ineff=
       F       F
Bank Sta=155.2,181.3
XS Rating Curve= 0 ,0
Exp/Cntr=0.3,0.1

Type RM Length L Ch R = 1 ,6940    ,354.8,362,363.5
XS GIS Cut Line= 3
2485434.81380311608271.8311583642485898.06814488608280.536084448
2486090.59382086 608454.13694634
#Sta/Elev= 30
       0 1726.85    22.6 1714.52    35.9 1710.59    71.9 1689.11    97.2 1671.82
     136 1641.23   152.2 1638.74   175.7 1637.15     200 1640.04   221.1 1638.78
     276 1639.42     284 1637.96     296 1636.34     316 1637.73     324 1642.12
     328  1642.8     384 1643.53     404  1647.6     436 1646.89   485.3 1649.29
   502.3 1648.67   520.6  1644.9   568.4 1645.93   593.5 1645.31   615.6 1643.33
     642  1644.7   672.2 1639.79   675.1 1640.52   701.2 1658.36   722.6 1669.48
#Mann= 8 ,-1 , 0
       0      .1       0   42.47      .1       0     284    .045       0
     316      .1       0  345.29     .12       0  446.23      .1       0
  595.11     .12       0  706.43      .1       0
#XS Ineff= 2 , 0
          267.16 1644.63  329.54         1647.62
Permanent Ineff=
       F       F
Bank Sta=284,316
XS Rating Curve= 0 ,0
Exp/Cntr=0.3,0.1

Type RM Length L Ch R = 1 ,6578    ,421,385.4,373
XS GIS Cut Line= 2
2485326.78889369608367.2215662712485961.23459714608822.504923745
#Sta/Elev= 30
       0 1751.97    34.4 1732.55    45.6 1724.09      59 1720.37    85.7  1700.9
   117.3 1673.74   157.2 1633.25   163.1 1629.66   177.4 1626.05     192 1626.83
     209  1633.6   216.6  1635.5   234.8 1635.68   300.7 1634.98   328.8 1633.04
   343.7 1637.51   354.4 1638.35   489.9 1635.82   526.7 1633.11   547.2 1637.69
   555.2  1638.3   590.2 1636.46   615.4  1637.1   620.3 1635.99   630.3 1631.18
   637.5 1631.01   649.8 1635.77   678.6 1655.77   713.8  1674.9   780.9 1703.05
#Mann= 3 ,-1 , 0
       0      .1       0   157.2    .045       0     209      .1       0
#XS Ineff= 2 , 0
                          354.17         1650.39
Permanent Ineff=
       F       F
Bank Sta=157.2,209
XS Rating Curve= 0 ,0
Exp/Cntr=0.3,0.1

Type RM Length L Ch R = 1 ,6193    ,160.1,252.7,416.9
XS GIS Cut Line= 2
2485107.58416764608776.4702438992485936.22795038608820.100076255
#Sta/Elev= 30
       0 1701.27    51.2 1678.18    99.3 1653.46   119.5 1640.14   135.3 1624.81
   139.4 1622.04   143.4 1620.72     153 1620.19   175.4  1617.6   286.61619.195
   295.6 1624.31   303.6 1626.67   359.2 1626.76   383.7 1629.04   391.7 1628.86
   408.7 1625.97   419.7 1627.18   439.8 1626.98   475.8  1630.5   531.9 1631.47
   547.9 1630.61     600 1633.24     624 1630.67   672.1 1628.85   692.1 1634.45
   712.1 1635.23   720.2 1637.71   748.2 1654.55   768.2 1665.28   829.8 1693.11
#Mann= 9 ,-1 , 0
       0      .1       0   49.43      .1       0   72.39      .1       0
     153    .045       0   286.6      .1       0  354.28     .12       0
  547.75      .1       0  557.52     .12       0  659.14      .1       0
Bank Sta=153,286.6
XS Rating Curve= 0 ,0
Exp/Cntr=0.3,0.1

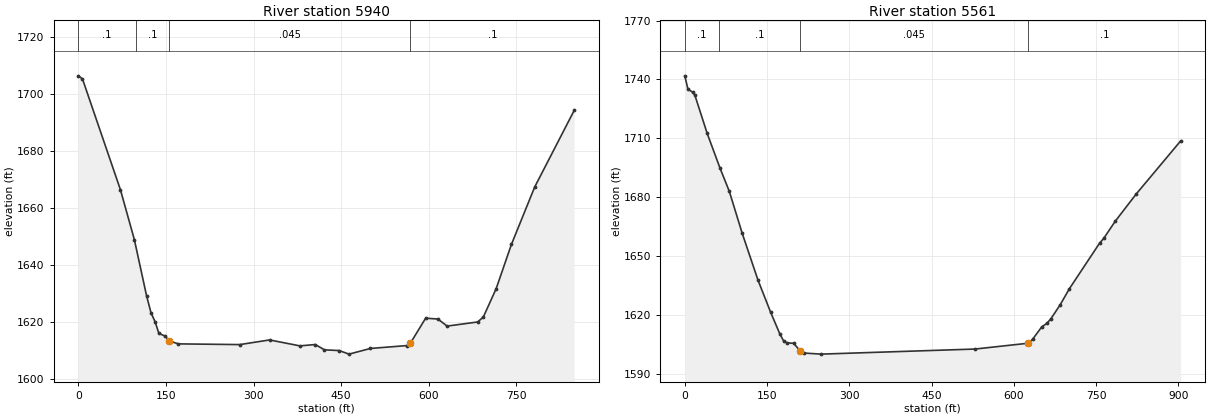
Type RM Length L Ch R = 1 ,5940    ,393.2,379.2,221.2
XS GIS Cut Line= 2
2485061.66023103608822.3080247922485708.44816948609372.220147896
#Sta/Elev= 30
       0 1706.34     7.1 1705.25    72.1 1666.43    95.9 1648.99   116.9 1629.25
   124.4 1623.37   131.7 1620.05   137.9 1616.11   148.7 1615.18   155.3  1613.5
   171.4 1612.45   276.4  1612.2   327.5 1613.83   379.4 1611.75   405.7 1612.22
   421.5 1610.36   446.7 1610.11   463.5 1608.86   500.2 1610.85   562.8 1611.86
   568.5 1612.66   594.7 1621.45   615.7 1621.15   631.5 1618.68     684 1620.13
   693.6 1621.91   715.5 1631.82   741.7 1647.35   781.5 1667.43     849  1694.2
#Mann= 4 ,-1 , 0
       0      .1       0   97.94      .1       0   155.3    .045       0
   568.5      .1       0
Bank Sta=155.3,568.5
XS Rating Curve= 0 ,0
Exp/Cntr=0.3,0.1

Type RM Length L Ch R = 1 ,5561    ,294,250.4,146.4
XS GIS Cut Line= 2
2484805.26537252 609205.278369312485668.61933255 609474.16210793
#Sta/Elev= 30
       0 1741.86     5.7 1735.07    14.1 1733.58    18.3 1732.05    40.8 1712.55
    64.4 1694.72    81.2 1683.01   104.7 1661.64   133.4 1637.87   156.6 1621.39
   173.3 1610.41   180.3 1606.79   185.9 1605.92   198.5 1605.58   210.1 1601.88
   216.5 1600.66   248.7  1600.1   529.4 1602.69   626.5 1605.66   634.2 1607.64
   650.9 1613.93   660.6  1615.8   667.7 1618.13   684.4 1625.12   701.2 1633.32
   756.4 1656.58     764 1659.04   785.1 1667.81   823.5 1681.74   904.3 1708.68
#Mann= 4 ,-1 , 0
       0      .1       0   62.76      .1       0   210.1    .045       0
   626.5      .1       0
Bank Sta=210.1,626.5
XS Rating Curve= 0 ,0
Exp/Cntr=0.3,0.1