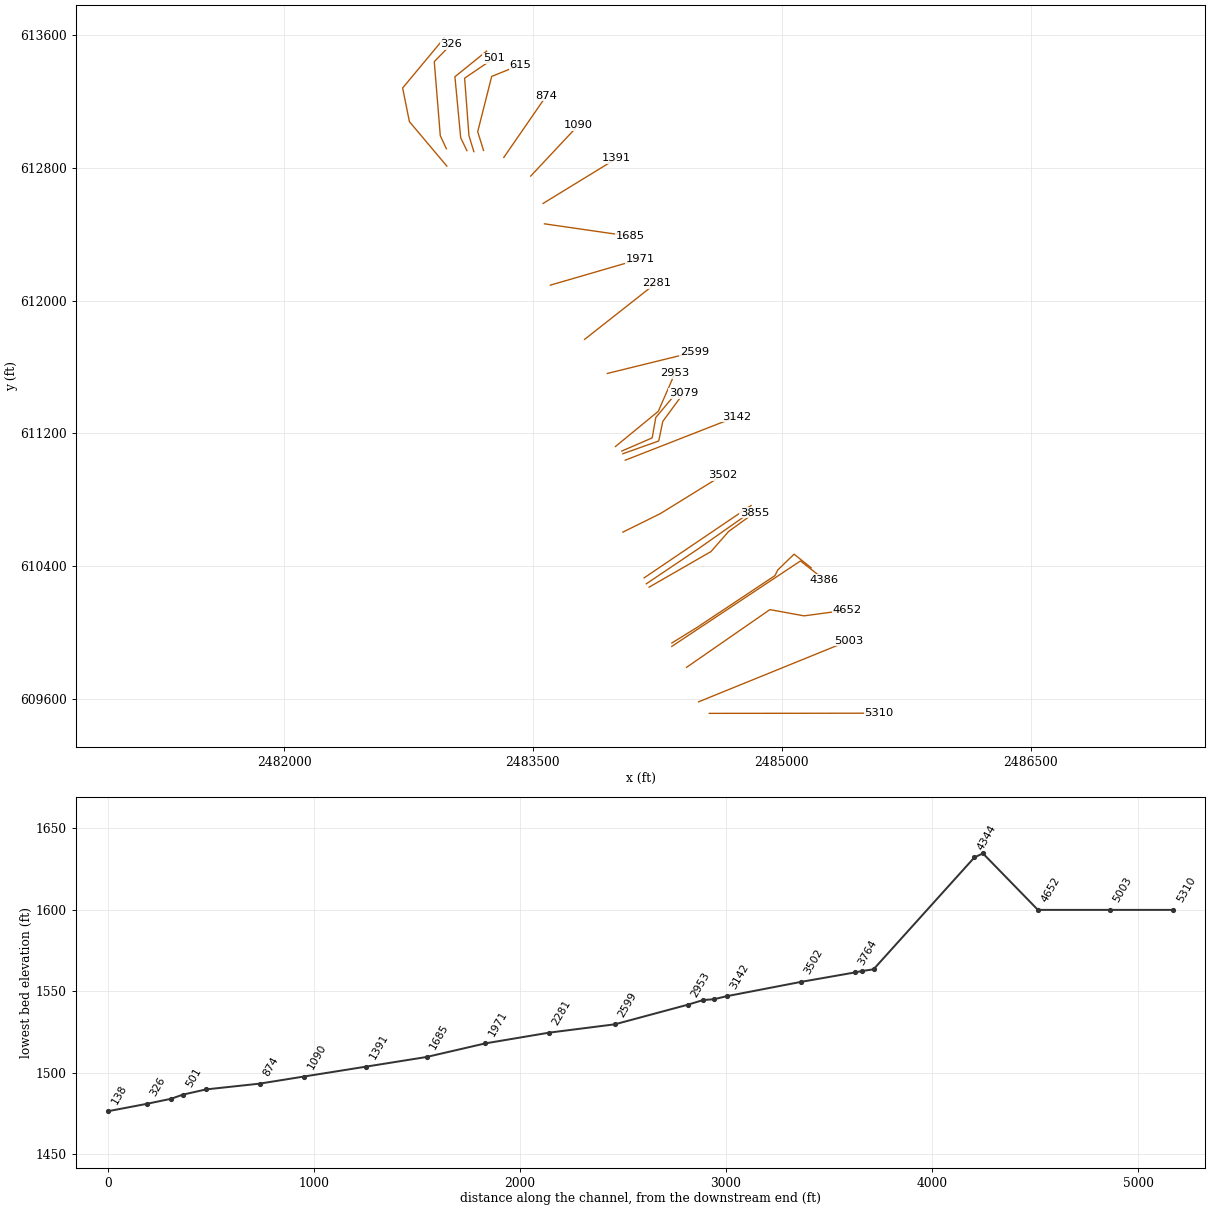
HEC-RAS study STONYRN1.prj: STONYRN1

--- STONYRN1.g01 (geometry) --- (continued)

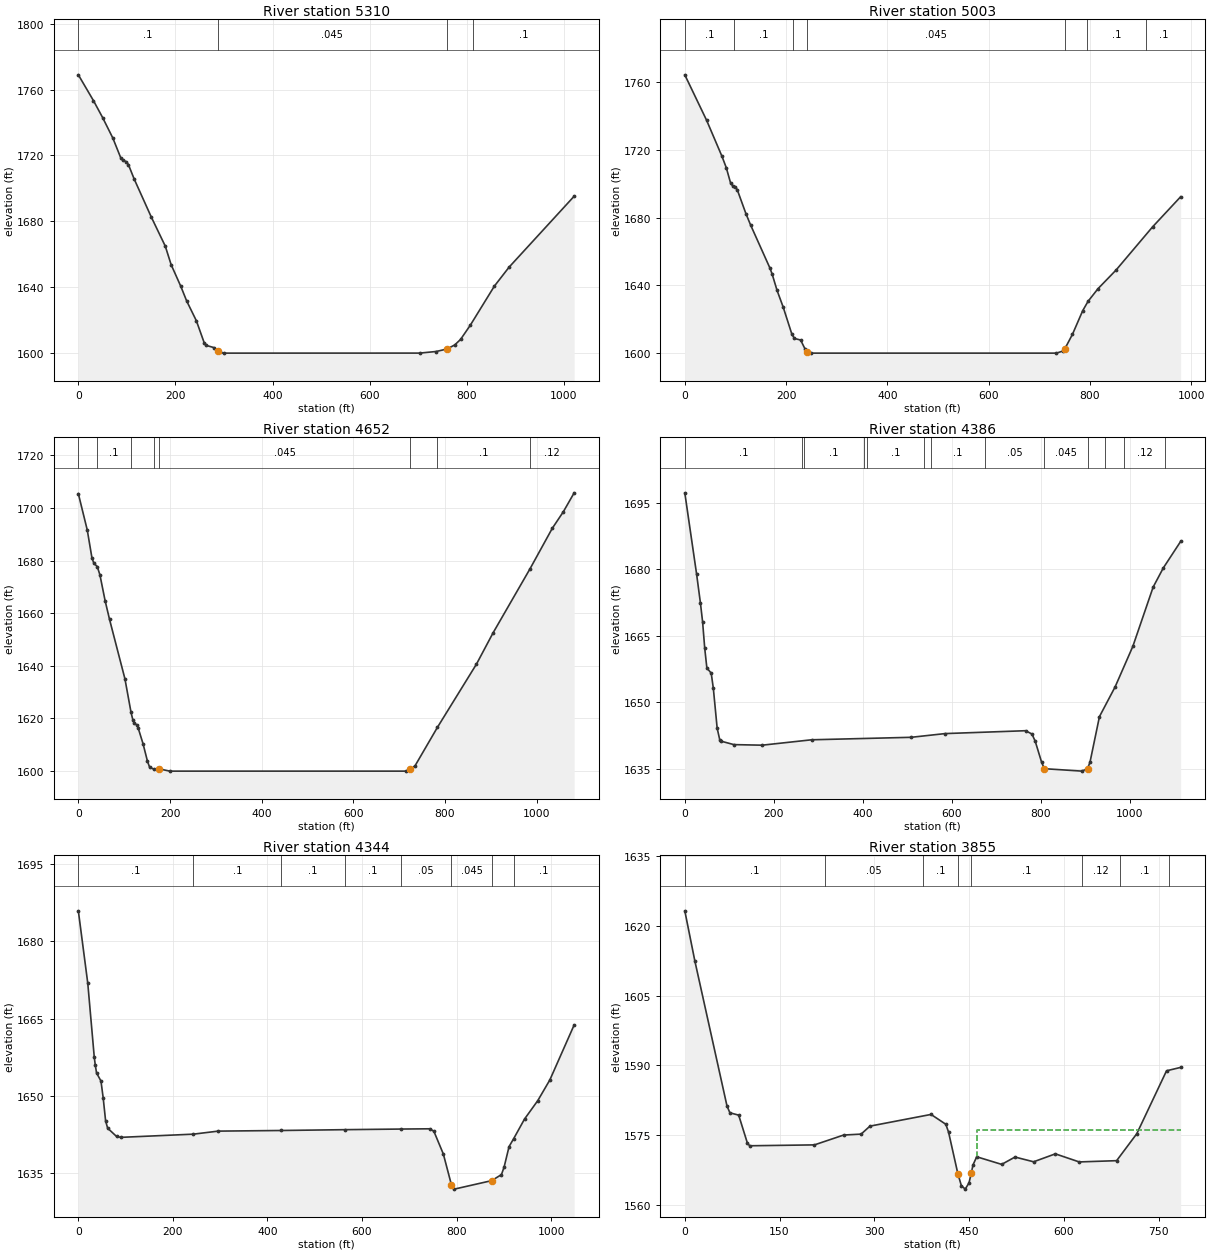
Type RM Length L Ch R = 1 ,5310    ,205.1,307.8,377.3
XS GIS Cut Line= 2
2484563.66291366609511.8012030352485584.77643086609512.920941655
#Sta/Elev= 30
       0 1769.07    31.1  1753.4    50.1 1743.02    71.1 1730.58    87.1 1718.77
    91.1 1717.36    99.1 1716.12   103.1 1714.46   115.1 1705.63     150 1682.72
   179.1 1664.83   191.1  1653.6   211.1 1640.36   223.1 1631.52   243.1 1619.45
   259.1 1606.16   263.1 1604.51   279.1 1603.16   287.1 1601.09   291.1 1600.18
   299.1 1599.78   703.1  1599.8   736.8 1600.77   759.1 1602.27   775.1 1604.75
   787.1 1608.09   807.1  1616.7   856.9 1640.58   887.1 1652.08  1021.1 1695.23
#Mann= 4 ,-1 , 0
       0      .1       0   287.1    .045       0   759.1    .025       0
  812.83      .1       0
Bank Sta=287.1,759.1
XS Rating Curve= 0 ,0
Exp/Cntr=0.3,0.1

Type RM Length L Ch R = 1 ,5003    ,264.8,350,299.7
XS GIS Cut Line= 2
2484498.86350438609581.3462829662485405.82810152609950.019550759
#Sta/Elev= 30
       0 1764.46    43.1 1737.53    73.3  1716.3    81.9 1709.51    90.5 1700.34
    94.9 1698.65    99.2 1698.27   103.5 1696.54   120.8 1682.22     130 1675.54
   168.3 1649.97   172.6 1646.42   182.2 1636.87   194.2 1627.07   211.4 1611.01
   216.5 1608.45   228.7 1607.53   237.8 1601.99   241.7 1600.29   248.4 1599.78
   733.9 1599.78   746.9 1601.06   750.2 1602.22   765.5 1610.95   785.7 1624.91
   796.2 1630.42   815.9 1637.92   851.5 1648.93   923.9 1674.58     979  1692.3
#Mann= 7 ,-1 , 0
       0      .1       0   96.91      .1       0  213.18    .055       0
   241.7    .045       0   750.2    .025       0  794.53      .1       0
   910.8      .1       0
Bank Sta=241.7,750.2
XS Rating Curve= 0 ,0
Exp/Cntr=0.3,0.1

Type RM Length L Ch R = 1 ,4652    ,655.2,266.9,305.6
XS GIS Cut Line= 4
2484426.75544883609789.3882712492484928.81910166610137.255946351
2485134.62564364610099.5782004412485394.01474687 610134.56296261
#Sta/Elev= 30
       0 1705.46    19.5  1691.6    29.8 1680.89    34.1 1678.88    41.3  1677.7
    47.1 1674.53    58.4 1664.71    68.1 1657.55   101.7 1634.91     115 1622.15
   118.9 1619.33   121.6 1618.16   127.6 1617.35   130.4 1616.29   141.1 1610.26
   150.8 1603.58   155.7 1601.18   164.2 1600.59   176.4 1600.63   199.5 1599.78
   714.4 1599.78   724.5 1600.44   734.8 1601.86   783.6 1616.49   868.6 1640.52
   904.9 1652.45   985.6 1676.88  1034.1 1692.27  1058.3  1698.6  1081.8 1705.78
#Mann= 8 ,-1 , 0
       0      .1       0    41.3      .1       0     115      .1       0
   164.2     .05       0   176.4    .045       0   724.5     .05       0
   783.6      .1       0   985.6     .12       0
Bank Sta=176.4,724.5
XS Rating Curve= 0 ,0
Exp/Cntr=0.3,0.1

Type RM Length L Ch R = 1 ,4386    ,34.2,41.5,54.2
XS GIS Cut Line= 3
2484337.38746748  609915.41561392485113.31995548610430.707648293
2485256.67303988610318.240868098
#Sta/Elev= 30
       0 1697.28    26.6 1678.86    35.2 1672.31      40 1668.12    44.8 1662.12
    49.6 1657.69    59.3 1656.56    64.1 1653.12    72.7  1644.1    78.5 1641.49
    81.4 1641.18   110.2  1640.4   173.7 1640.27   284.9 1641.49   508.4 1642.05
   584.7 1642.89   765.5 1643.54   779.9 1642.78   787.2 1641.13   801.6 1636.37
   807.81634.959   892.2 1634.41   904.61634.974   910.1 1636.41   931.4 1646.73
   966.5 1653.43  1006.4  1662.6    1052 1675.99  1074.8 1680.31  1113.7 1686.29
#Mann= 13 ,-1 , 0
       0      .1       0  264.01     .05       0  267.42      .1       0
   402.7     .05       0   408.7      .1       0  537.98     .05       0
   553.4      .1       0  673.26     .05       0   807.8    .045       0
   904.6     .05       0  943.82      .1       0  987.48     .12       0
  1079.1      .1       0
Bank Sta=807.8,904.6
XS Rating Curve= 0 ,0
Exp/Cntr(USF)=0,0
Exp/Cntr=0.3,0.1

Type RM Length L Ch R = 1 ,4344    ,464.2,489.4,507.2
XS GIS Cut Line= 6
2484338.04602198609936.1161750022484489.13297629610029.601227981
2484959.39112158610342.1623647122484976.38840394610376.156929432
2485074.59492425610471.5305693412485177.52291187610389.377037934
#Sta/Elev= 30
       0 1685.91      20 1671.84    33.7 1657.54    35.7  1656.1    38.5 1654.48
    47.9  1652.9    52.6 1649.62    57.7 1645.18      62 1643.76    80.8 1642.16
    89.7 1641.98   243.3  1642.6   295.9 1643.19   429.1 1643.31   563.7 1643.47
   681.8 1643.59   743.1 1643.64   752.1 1643.17   772.2 1638.74   789.2  1632.8
   795.3 1631.94   874.5 1633.59   895.1 1634.76   900.7 1636.21   911.2 1640.19
   920.6 1641.67   943.9 1645.53   971.9  1649.1   997.5 1653.12  1048.9 1663.78
#Mann= 8 ,-1 , 0
       0      .1       0   243.3      .1       0   429.1      .1       0
   563.7      .1       0   681.8     .05       0   789.2    .045       0
   874.5     .05       0   920.6      .1       0
Bank Sta=789.2,874.5
XS Rating Curve= 0 ,0
Exp/Cntr(USF)=0,0
Exp/Cntr=0.3,0.1

Type RM Length L Ch R = 1 ,3855    ,57.5,54,52.4
XS GIS Cut Line= 4
 2484200.8429779610272.6246389152484573.63759107610487.042455642
2484679.85045372610608.1544450782484836.83703374610721.690199969
#Sta/Elev= 30
       0 1623.29      16 1612.43    66.8 1581.25    71.4 1579.78    85.3 1579.28
    99.1 1573.25   102.7 1572.68   205.2 1572.87   251.4 1574.99   279.1 1575.19
   293.1 1576.91   389.8 1579.43   413.2 1577.31   417.5 1575.64  432.221566.692
   437.8 1564.08   443.9 1563.34   449.9 1564.68   453.4 1566.72   456.2 1568.54
   462.1 1570.31   501.6 1568.67   522.7 1570.25   552.2 1569.23   586.6 1570.94
   624.3  1569.2   683.6 1569.47   715.5 1575.28   762.6 1588.83   784.9 1589.56
#Mann= 8 ,-1 , 0
       0      .1       0   221.4     .05       0  377.28      .1       0
  432.22    .045       0   453.4      .1       0  628.07     .12       0
  688.46      .1       0  766.23     .12       0
#XS Ineff= 2 , 0
                          462.74        1576.114
Permanent Ineff=
       F       F
Bank Sta=432.22,453.4
XS Rating Curve= 0 ,0
Exp/Cntr(USF)=0,0
Exp/Cntr=0.3,0.1

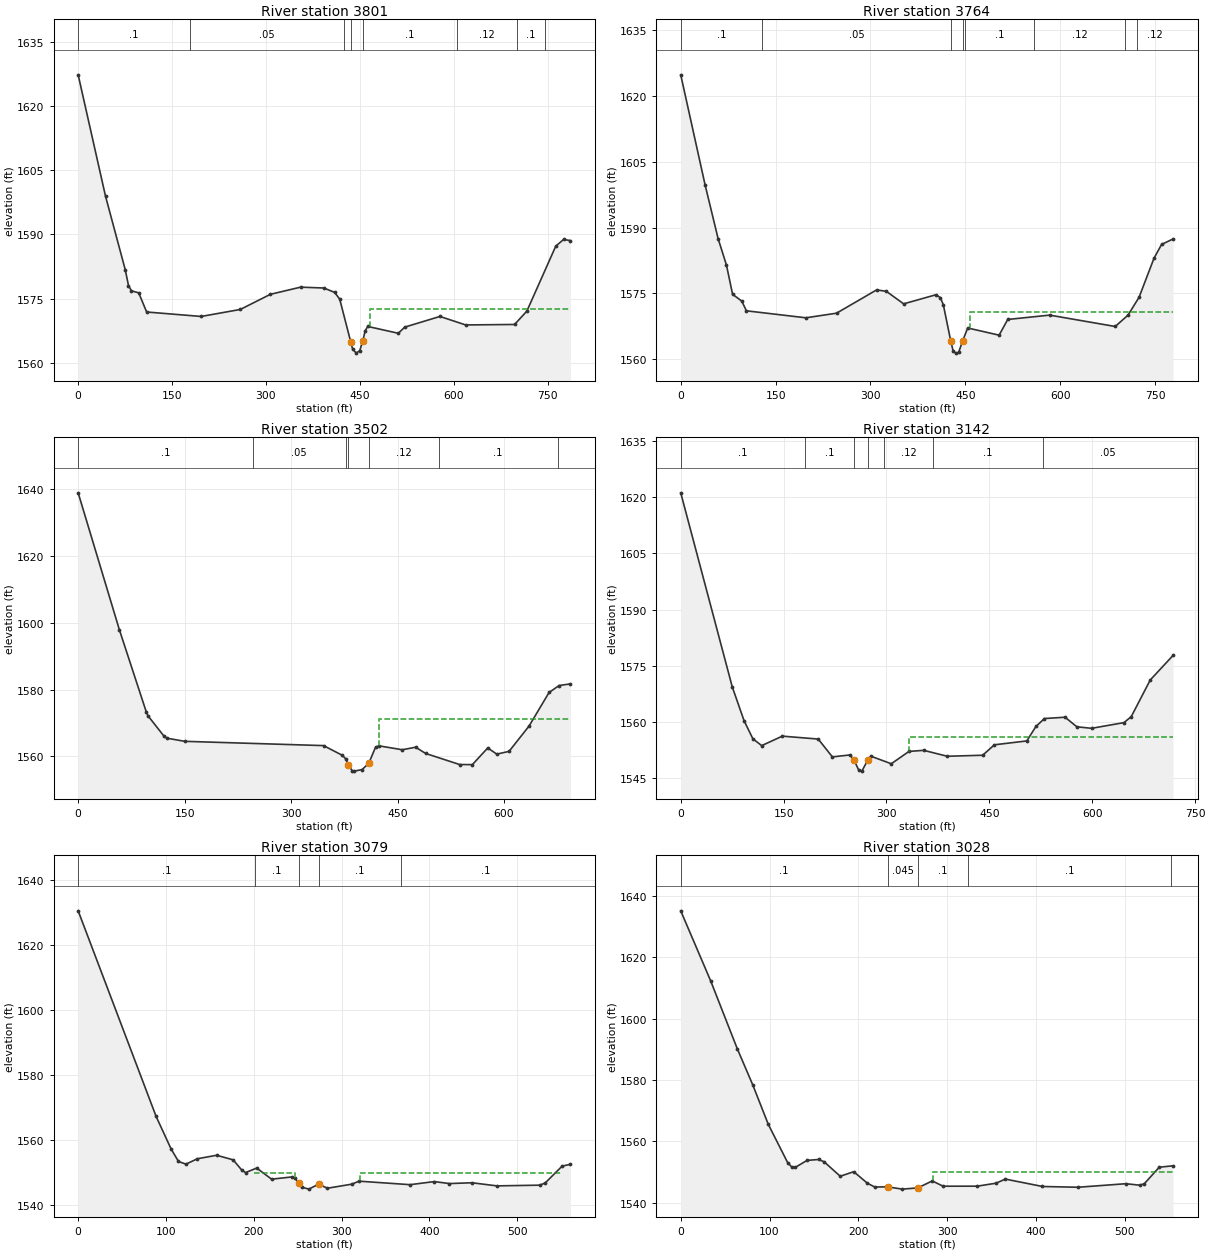
Type RM Length L Ch R = 1 ,3801    ,37,36.8,36.6
XS GIS Cut Line= 3
2484184.04885739610292.8717900672484500.31179061610505.947251366
2484831.73784904610738.687482329
#Sta/Elev= 30
       0 1627.27    43.7 1598.94    75.2 1581.79    80.4 1578.08    85.2 1576.84
    96.7 1576.39   109.4 1571.91   196.5 1570.87   258.9  1572.5   307.1 1576.04
   355.3 1577.71   392.4 1577.51   409.6 1576.49   417.8 1574.91   435.5 1564.85
   438.3 1563.29   444.1 1562.31   449.8  1562.9   454.61565.142   458.4  1567.5
   462.5 1568.54   511.4 1566.94   521.6 1568.38   577.9 1570.87   618.9 1568.89
   697.1    1569   716.7 1572.12   762.8 1587.26   775.3 1588.84   786.3 1588.58
#Mann= 8 ,-1 , 0
       0      .1       0  178.24     .05       0  424.18      .1       0
   435.5    .045       0   454.6      .1       0  604.58     .12       0
  701.34      .1       0   745.4     .12       0
#XS Ineff= 2 , 0
                          466.36         1572.59
Permanent Ineff=
       F       F
Bank Sta=435.5,454.6
XS Rating Curve= 0 ,0
Exp/Cntr(USF)=0,0
Exp/Cntr=0.3,0.1

Type RM Length L Ch R = 1 ,3764    ,261.8,261.6,260.5
XS GIS Cut Line= 2
2484170.84950373610328.6555669032484815.59043079610765.033269987
#Sta/Elev= 30
       0 1624.82    38.5 1599.76    59.1  1587.5    72.3 1581.48      82 1574.82
    96.5 1573.27   103.9 1571.05   197.9 1569.46   246.4 1570.51   309.7 1575.81
   325.1  1575.5   352.5 1572.64   403.6 1574.71   410.6 1574.05   415.3 1572.42
  427.091564.116   430.7 1561.94   434.6 1561.41   439.4 1561.56   445.81564.178
   453.8 1567.14   503.5  1565.5   517.1 1569.08   583.4 1570.07   687.1 1567.48
   707.3 1570.06   724.8 1574.13   748.5 1583.05   760.4 1586.17   778.5 1587.42
#Mann= 8 ,-1 , 0
       0      .1       0  129.02     .05       0  427.09    .045       0
   445.8     .05       0  449.63      .1       0  559.19     .12       0
  702.58      .1       0  722.29     .12       0
#XS Ineff= 2 , 0
                           457.9         1570.77
Permanent Ineff=
       F       F
Bank Sta=427.09,445.8
XS Rating Curve= 0 ,0
Exp/Cntr=0.3,0.1

Type RM Length L Ch R = 1 ,3502    ,360.2,359.9,353.7
XS GIS Cut Line= 3
2484042.69860836610604.4068308092484268.13090439610715.729299195
2484644.36241357610948.127389953
#Sta/Elev= 30
       0 1638.93      58 1597.99    95.9  1573.4    98.2 1572.23   120.5 1566.21
     125 1565.48   150.2 1564.54   345.7 1563.26     372 1560.38   376.7 1559.36
   380.6 1557.58   386.1  1555.7   389.3 1555.62   400.2  1556.1   409.6 1558.02
   409.6 1558.03     419 1562.78   423.8 1563.19   456.7 1562.02   475.5 1562.78
   489.6 1560.91   537.5 1557.59   555.4 1557.57   577.1 1562.56   589.8 1560.71
   607.1 1561.53   635.3 1569.12   663.5 1579.17   677.6 1581.24   693.6 1581.74
#Mann= 7 ,-1 , 0
       0      .1       0  245.91     .05       0   376.9     .12       0
   380.6    .045       0   409.6     .12       0  508.32      .1       0
  675.43     .12       0
#XS Ineff= 2 , 0
                          424.54         1571.36
Permanent Ineff=
       F       F
Bank Sta=380.6,409.6
XS Rating Curve= 0 ,0
Exp/Cntr=0.3,0.1

Type RM Length L Ch R = 1 ,3142    ,54.1,63.3,74.5
XS GIS Cut Line= 2
2484056.80130741611037.8546295432484725.32412167 611299.29090618
#Sta/Elev= 30
       0 1621.15    75.1 1569.37    92.3 1560.34   105.2 1555.49   118.1 1553.67
   148.1  1556.2   200.5 1555.42   221.1 1550.66   246.9 1551.18   252.4 1549.93
   259.8 1547.03   264.1 1546.86   272.7  1549.8     277 1550.86     307 1548.83
   332.8 1552.12   354.3 1552.41   388.6 1550.83   440.2  1551.1   457.4 1553.89
   504.6 1554.92   517.9 1558.78   530.4  1560.9   560.4 1561.25   577.6 1558.69
   599.1 1558.29   646.3 1559.81   656.9 1561.41   684.6 1571.19   717.8 1577.74
#Mann= 7 ,-1 , 0
       0      .1       0  181.59      .1       0   252.4    .045       0
   272.7      .1       0  296.94     .12       0  367.38      .1       0
  527.63     .05       0
#XS Ineff= 2 , 0
                          332.23          1556.1
Permanent Ineff=
       F       F
Bank Sta=252.4,272.7
XS Rating Curve= 0 ,0
Exp/Cntr=0.5,0.3

Type RM Length L Ch R = 1 ,3079    ,48.5,51.1,55.4
XS GIS Cut Line= 4
2484043.06307865611077.0937999712484258.76118045611153.734052304
2484283.33611562611271.9712722512484408.35046705611442.053100416
#Sta/Elev= 30
       0 1630.61    88.8 1567.35   105.8 1557.37   114.3 1553.48   122.8 1552.65
   135.8 1554.32   157.8 1555.39   176.6 1553.98   186.4 1550.82   190.7 1550.07
   203.4 1551.45   220.4 1548.03   243.4 1548.72   246.8 1548.44   251.1 1546.82
   254.6 1545.58   262.8 1544.97   273.8 1546.49     284 1545.25   311.8  1546.5
     320 1547.42   378.1 1546.34   405.7 1547.29     423 1546.68   448.6 1546.93
     477 1545.97   525.9 1546.19     532 1546.86   551.3 1552.04   560.8 1552.62
#Mann= 5 ,-1 , 0
       0      .1       0  201.01      .1       0   251.1    .045       0
   273.8      .1       0  367.87      .1       0
#XS Ineff= 4 ,-1
     200   247.5    1550   247.5     251    1545   273.8     321    1545
     321     550    1550
Permanent Ineff=
       F       F       F       F
Bank Sta=251.1,273.8
XS Rating Curve= 0 ,0
Exp/Cntr(USF)=0,0
Exp/Cntr=0.5,0.3

Type RM Length L Ch R = 1 ,3028    ,84.7,75.2,61.1
XS GIS Cut Line= 4
 2484036.2665935611093.102580983 2484219.4502368611172.579312241
2484240.88280321611295.0958833762484388.65470844611471.596738322
#Sta/Elev= 30
       0 1635.04    33.7 1612.26    63.7 1590.16    81.2 1578.34    98.6 1565.57
   120.4 1553.12   124.8 1551.76   129.1  1551.6   142.2 1553.84   155.3 1554.15
   161.4 1553.41   179.6 1548.69   194.8 1550.17   210.1 1546.44   218.4 1545.19
   232.9 1545.24   249.5  1544.5     267  1544.9   283.2 1547.17   295.4 1545.45
   333.8 1545.46   355.1 1546.43   365.5 1547.77   407.3 1545.36   447.3 1545.11
   501.2 1546.26   516.8 1545.78     522 1546.27   538.8 1551.63   554.3 1552.09
#Mann= 5 ,-1 , 0
       0      .1       0   232.9    .045       0     267      .1       0
  323.87      .1       0  551.67     .05       0
#XS Ineff= 2 , 0
                           283.6         1549.97
Permanent Ineff=
       F       F
Bank Sta=232.9,267
XS Rating Curve= 0 ,0
Exp/Cntr(USF)=0,0
Exp/Cntr=0.5,0.3

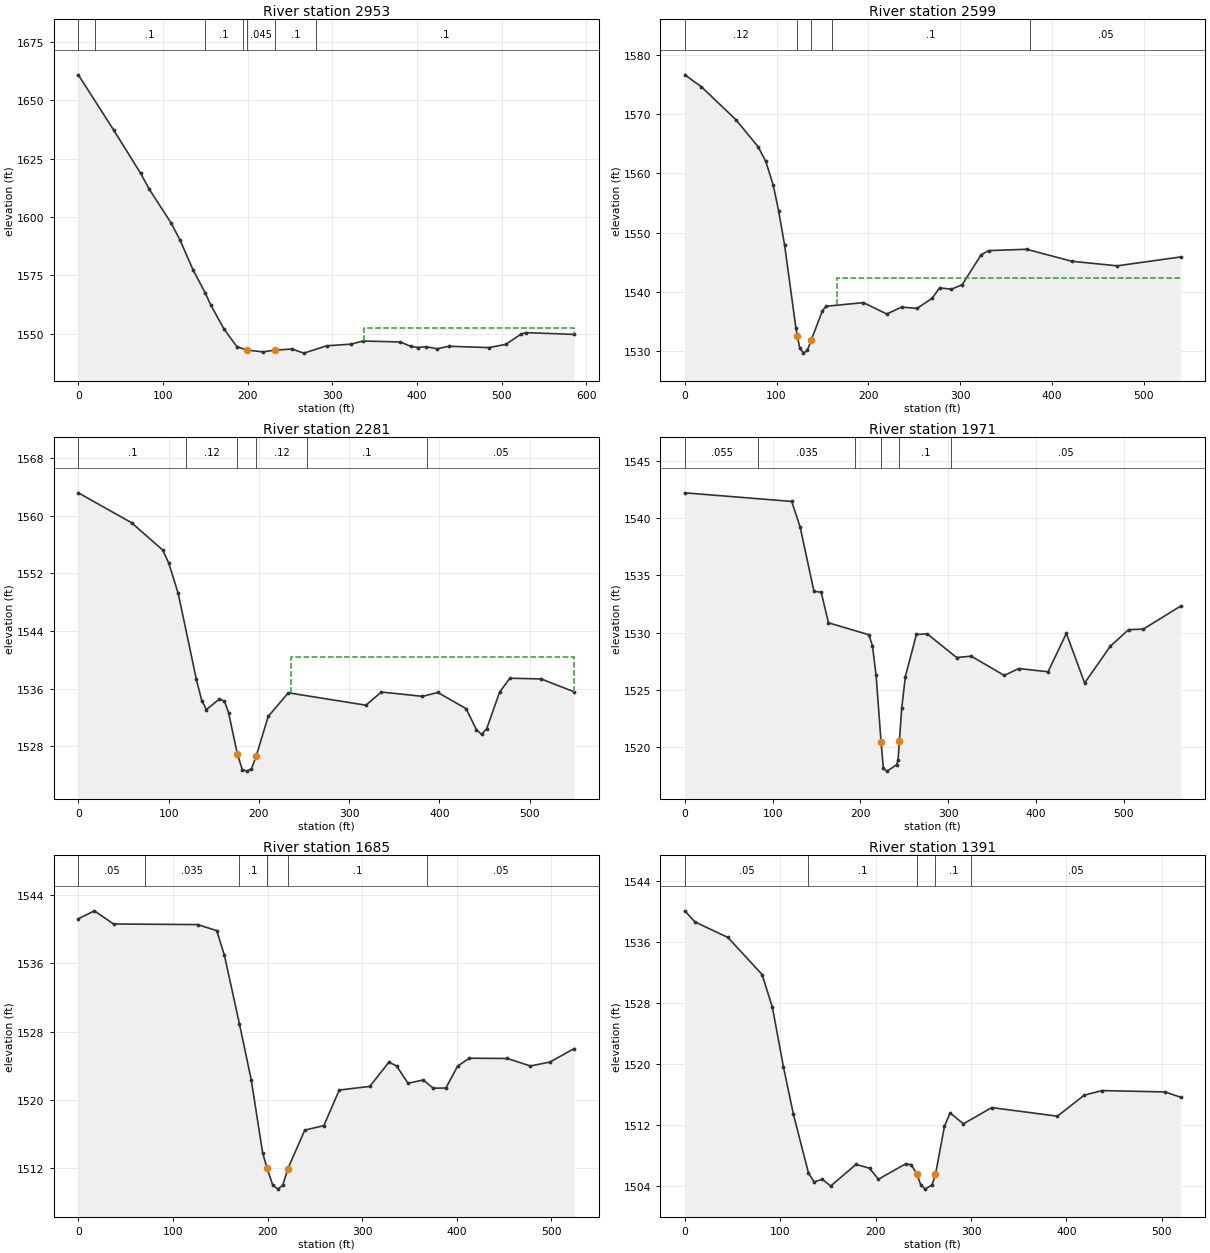
Type RM Length L Ch R = 1 ,2953    ,358.9,353.6,343.6
XS GIS Cut Line= 3
2483997.98198669611120.501298126 2484256.1165134611332.694938258
2484356.81566826611563.259773645
#Sta/Elev= 30
       0 1660.86    41.6 1637.29    73.5 1618.72    83.8 1611.88   109.7 1597.32
   120.1 1590.12   135.6 1577.26     150 1567.36   156.3  1562.4   171.9 1552.04
   187.4 1544.37     199 1542.97   217.9 1542.16   232.4  1542.9   252.3 1543.38
   266.5 1541.62   293.5 1544.77     322 1545.46   336.6 1546.81   380.4 1546.41
   392.5 1544.55   401.6 1544.02   410.8 1544.38   423.8 1543.49   438.1 1544.57
     485 1543.99   504.9 1545.36   523.1 1549.76   528.6 1550.41   585.8 1549.64
#Mann= 7 ,-1 , 0
       0      .1       0   19.49      .1       0  150.22      .1       0
  194.17      .1       0     199    .045       0   232.4      .1       0
  280.96      .1       0
#XS Ineff= 2 , 0
                          337.37         1552.26
Permanent Ineff=
       F       F
Bank Sta=199,232.4
XS Rating Curve= 0 ,0
Exp/Cntr=0.3,0.1

Type RM Length L Ch R = 1 ,2599    ,313.8,318.4,321.9
XS GIS Cut Line= 2
2483949.14221561611560.896357086     2484473.837      611689.896
#Sta/Elev= 30
       0 1576.66    18.1 1574.64    55.9 1569.04    79.9  1564.5    88.2 1562.03
    96.4 1558.01   102.2  1553.7   108.8 1547.85   121.1 1533.82   122.81532.431
   125.2 1530.47   129.3 1529.61   133.5 1530.07   137.81531.816   149.9 1536.76
   154.1 1537.53   194.7 1538.15     220 1536.23   236.4  1537.4   252.9 1537.17
   269.4 1538.86   277.6 1540.64   290.6 1540.42   302.3 1541.18   322.9 1546.24
   331.2 1546.94   372.4 1547.17   421.8 1545.14   471.2 1544.37   540.3 1545.87
#Mann= 5 ,-1 , 0
       0     .12       0   122.8    .045       0   137.8     .12       0
  160.49      .1       0  376.31     .05       0
#XS Ineff= 2 , 0
                          165.64         1542.36
Permanent Ineff=
       F       F
Bank Sta=122.8,137.8
XS Rating Curve= 0 ,0
Exp/Cntr=0.3,0.1

Type RM Length L Ch R = 1 ,2281    ,312.5,309.5,304.2
XS GIS Cut Line= 2
 2483812.0361011 611766.333166322484243.51040648612106.101907989
#Sta/Elev= 30
       0 1563.21    59.1 1559.04    93.5 1555.25   100.2 1553.42   110.6 1549.24
   130.7 1537.29   136.7 1534.32   141.9 1533.07   156.1 1534.53   161.8 1534.24
   166.4 1532.65   176.1 1526.91   181.6 1524.73   186.7 1524.51   191.8 1524.85
   196.9 1526.55   210.3 1532.11   232.6  1535.4   318.5 1533.68   335.6 1535.51
   381.2 1534.91   398.2 1535.45   429.6 1533.19     441 1530.25   446.7 1529.62
   452.4 1530.43   466.6 1535.49     478 1537.43   512.6 1537.33   549.2 1535.54
#Mann= 6 ,-1 , 0
       0      .1       0  119.71     .12       0   176.1    .045       0
   196.9     .12       0  252.97      .1       0  386.23     .05       0
#XS Ineff= 2 , 0
                          236.11         1540.37
Permanent Ineff=
       F       F
Bank Sta=176.1,196.9
XS Rating Curve= 0 ,0
Exp/Cntr=0.3,0.1

Type RM Length L Ch R = 1 ,1971    ,290.7,286.2,281.5
XS GIS Cut Line= 2
2483605.59907734612093.2212997922484147.65670021612250.828385744
#Sta/Elev= 30
       0 1542.21   121.7 1541.46   131.4  1539.2     147 1533.63   155.3 1533.53
   163.6 1530.87   209.5 1529.83   213.6 1528.89   217.8 1526.29   223.41520.512
   226.1 1518.16   230.3 1517.93   241.1 1518.48   242.8 1518.89   244.3 1520.59
     247 1523.44   251.1 1526.18   263.7 1529.85   276.1  1529.9   309.5 1527.84
   326.1 1527.96   363.7 1526.28   380.3 1526.88   413.6  1526.6   434.4 1529.95
   455.2 1525.62   484.4 1528.82   505.2 1530.27     522 1530.32   564.5 1532.33
#Mann= 6 ,-1 , 0
       0    .055       0   83.52    .035       0  193.48      .1       0
   223.4    .045       0   244.3      .1       0  303.45     .05       0
Bank Sta=223.4,244.3
XS Rating Curve= 0 ,0
Exp/Cntr=0.3,0.1

Type RM Length L Ch R = 1 ,1685    ,286.6,294.3,300.4
XS GIS Cut Line= 2
2483569.91112289612462.8152978252484088.50893855 612387.95935805
#Sta/Elev= 30
       0 1541.23      17 1542.16    37.2 1540.62   126.1 1540.55   146.3 1539.84
   154.4 1536.94   170.2 1528.95   182.7 1522.39   194.8 1513.81   199.4 1512.03
   205.5 1510.02     211 1509.57   216.1 1510.05  221.381511.943   239.3 1516.48
   259.5 1517.01   275.7 1521.17     308  1521.6   328.2 1524.43   336.3    1524
   348.4 1521.97   364.6 1522.35     375 1521.39   388.4 1521.41   400.9 1523.98
   413.1  1524.9   453.5 1524.87   477.7 1523.99   498.6 1524.46     524 1526.03
#Mann= 6 ,-1 , 0
       0     .05       0   70.51    .035       0  169.84      .1       0
   199.4    .045       0  221.38      .1       0   368.5     .05       0
Bank Sta=199.4,221.38
XS Rating Curve= 0 ,0
Exp/Cntr=0.3,0.1

Type RM Length L Ch R = 1 ,1391    ,296,300.7,298.5
XS GIS Cut Line= 2
2483561.70594387612585.7373028212484004.80585744612857.041587467
#Sta/Elev= 30
       0 1540.12    10.6 1538.67    45.2 1536.63      81 1531.77    91.8 1527.47
   103.4 1519.65   113.8 1513.47   129.6 1505.76   135.4 1504.59   144.1 1504.92
   152.9 1504.05   179.4 1506.88   193.6 1506.38   202.9 1504.94   231.4 1506.95
   237.2 1506.85     243 1505.68   247.3 1504.21   251.8 1503.64   259.2 1504.21
   262.7 1505.57   272.1 1511.87     278 1513.63     292  1512.2   321.6 1514.33
   390.5  1513.2   418.6 1515.96   437.4 1516.56   503.1 1516.38   519.6 1515.69
#Mann= 5 ,-1 , 0
       0     .05       0   129.6      .1       0     243    .045       0
   262.7      .1       0  300.09     .05       0
Bank Sta=243,262.7
XS Rating Curve= 0 ,0
Exp/Cntr=0.3,0.1

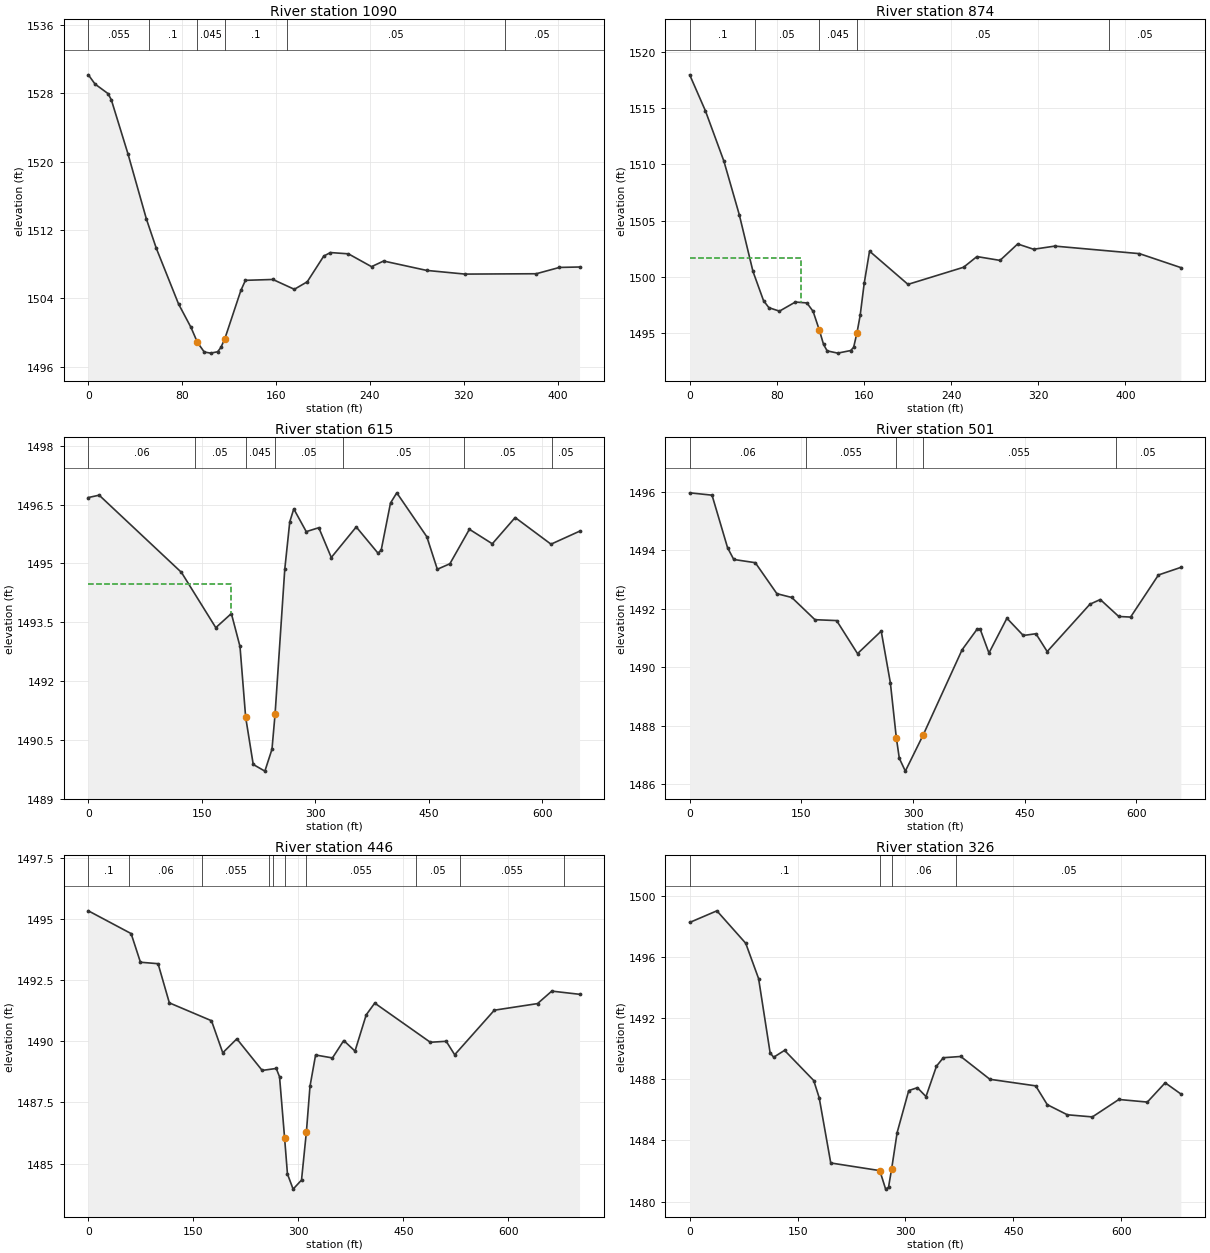
Type RM Length L Ch R = 1 ,1090    ,213.5,215.6,218.4
XS GIS Cut Line= 2
2483487.18683112612750.7411248582483773.47615723613056.315266944
#Sta/Elev= 30
       0 1530.16     5.7 1529.08    16.8 1527.96    19.6 1527.23    33.8  1520.9
    49.5 1513.28    57.9 1509.87    76.9 1503.34    87.5  1500.6      93 1498.84
    98.8 1497.72   104.3 1497.59   110.2 1497.75     113 1498.25   116.4  1499.3
     130 1504.92   133.9 1506.11   157.3 1506.21   175.6 1505.06   186.6 1505.94
   200.7 1508.95   206.4 1509.36   221.7 1509.21   241.4 1507.71   251.7 1508.37
   288.4 1507.27   321.1 1506.84   381.8 1506.88   401.6 1507.62   418.7 1507.67
#Mann= 6 ,-1 , 0
       0    .055       0   51.45      .1       0      93    .045       0
   116.4      .1       0  169.52     .05       0   355.2     .05       0
Bank Sta=93,116.4
XS Rating Curve= 0 ,0
Exp/Cntr=0.3,0.1

Type RM Length L Ch R = 1 ,874     ,251.3,259.1,264.9
XS GIS Cut Line= 2
2483324.92104193612863.0643938452483581.05815681613234.113160203
#Sta/Elev= 30
       0 1517.95    14.4 1514.76    31.4 1510.28    45.5 1505.53    58.1 1500.48
    67.8 1497.88    72.7 1497.26    82.4 1496.95      97 1497.76   107.6 1497.68
   113.3 1496.93   119.1 1495.24   122.9 1493.99   126.2 1493.42   135.9 1493.22
   147.8 1493.45   150.5 1493.73   153.6 1495.04   156.5 1496.57   160.2 1499.42
   165.1 1502.28   200.4 1499.33   251.4 1500.85   263.7  1501.8   284.9 1501.46
   301.1 1502.92   315.7 1502.45   335.2 1502.73   412.9 1502.06   450.9 1500.82
#Mann= 5 ,-1 , 0
       0      .1       0    59.9     .05       0   119.1    .045       0
   153.6     .05       0  384.87     .05       0
#XS Ineff= 2 , 0
          102.54 1501.67
Permanent Ineff=
       F       F
Bank Sta=119.1,153.6
XS Rating Curve= 0 ,0
Exp/Cntr=0.3,0.1

Type RM Length L Ch R = 1 ,615     ,113.4,113.9,121.8
XS GIS Cut Line= 4
2483202.78752088612905.2836550182483167.59430184613018.142680993
2483251.81803698613351.3385887692483425.70531718613421.527605322
#Sta/Elev= 30
       0 1496.68    14.3 1496.74   123.1 1494.77   168.5 1493.36   189.1 1493.72
   200.5 1492.88  207.981491.077     218 1489.87   233.4  1489.7   242.8 1490.26
   246.9 1491.16   259.7 1494.85   266.3 1496.06   271.6 1496.39   288.1 1495.81
   304.7 1495.91   321.2 1495.15   354.2 1495.93     383 1495.26   387.2 1495.34
   399.5 1496.54   407.8  1496.8   447.5 1495.68   461.4 1494.85     478 1494.99
   503.8 1495.87   534.1  1495.5   564.3 1496.17   611.7 1495.49   649.4 1495.82
#Mann= 7 ,-1 , 0
       0     .06       0  140.68     .05       0  207.98    .045       0
   246.9     .05       0   336.6     .05       0   497.1     .05       0
  613.19     .05       0
#XS Ineff= 2 , 0
          188.34 1494.47
Permanent Ineff=
       F       F
Bank Sta=207.98,246.9
XS Rating Curve= 0 ,0
Exp/Cntr=0.5,0.3

Type RM Length L Ch R = 1 ,501     ,55.3,55.8,55.2
XS GIS Cut Line= 4
2483144.13535702612898.2347020712483114.78885913612994.364081694
2483088.68176175613340.8743698252483263.83240065613459.667292077
#Sta/Elev= 30
       0 1495.97      30 1495.89    50.9 1494.09    59.2 1493.69    88.1 1493.58
   117.1 1492.52   137.1 1492.39   168.2 1491.63   197.3  1491.6   225.4 1490.47
   257.2 1491.24   269.5 1489.47   277.5 1487.59   281.5 1486.89   289.6 1486.45
   313.6 1487.69   365.8  1490.6   385.8  1491.3   389.9 1491.32   401.9 1490.49
     426 1491.68     448 1491.09     465 1491.15   480.1 1490.54   537.5 1492.16
   551.4 1492.32   576.2 1491.74   592.1 1491.72   629.5 1493.16   659.6 1493.42
#Mann= 5 ,-1 , 0
       0     .06       0  155.92    .055       0   277.5    .045       0
   313.6    .055       0  571.99     .05       0
#XS Ineff= 2 , 0
          258.28 1491.05  382.82         1491.09
Permanent Ineff=
       F       F
Bank Sta=277.5,313.6
XS Rating Curve= 0 ,0
Exp/Cntr=0.5,0.3

Type RM Length L Ch R = 1 ,446     ,119.4,119.2,119.1
XS GIS Cut Line= 4
2483102.39695941612903.8533673222483065.08532845612981.425283042
2483030.18166131613349.4750734012483221.38920338613503.914227731
#Sta/Elev= 30
       0 1495.33    61.1  1494.4    74.4 1493.23    99.6 1493.17   115.7 1491.57
   175.9 1490.84     192 1489.53   212.1  1490.1   248.3 1488.81   268.4 1488.89
   273.1 1488.55   280.3 1486.06   284.4 1484.58   292.5 1483.96   304.5 1484.33
   311.5 1486.31   316.6 1488.16   324.6 1489.44   348.7 1489.32   364.8 1490.03
   380.9  1489.6   396.9 1491.08   409.1 1491.56   488.5 1489.96   511.2    1490
   523.3 1489.45   579.9 1491.27   641.6 1491.54     662 1492.05   701.6 1491.92
#Mann= 10 ,-1 , 0
       0      .1       0   57.98     .06       0  162.81    .055       0
  257.93      .1       0  263.44    .055       0   280.3    .045       0
   311.5    .055       0  467.45     .05       0  530.65    .055       0
  679.47     .05       0
Bank Sta=280.3,311.5
XS Rating Curve= 0 ,0
Exp/Cntr(USF)=0,0
Exp/Cntr=0.5,0.3

Type RM Length L Ch R = 1 ,326     ,188.2,187.9,188.6
XS GIS Cut Line= 4
2482978.83336937612915.3626446932482942.01960218612993.754031891
2482905.76150112613440.4538370322483009.05024746613546.475250848
#Sta/Elev= 30
       0 1498.25    37.8 1499.01    77.9 1496.89    95.8 1494.58   111.8 1489.73
   116.7 1489.44   131.9 1489.89   172.4 1487.92     180  1486.8   196.1 1482.53
   264.3 1482.03   272.4 1480.82   276.4 1480.94   280.8 1482.16   288.4 1484.52
   304.5 1487.26   316.5 1487.45   328.5 1486.87   343.1 1488.86   352.6 1489.41
   376.9 1489.49   417.3    1488     481 1487.57   497.1 1486.34     525 1485.68
   559.8 1485.54   596.6 1486.68   636.2 1486.51     661 1487.77   682.8 1487.04
#Mann= 4 ,-1 , 0
       0      .1       0   264.3    .045       0   280.8     .06       0
  370.55     .05       0
Bank Sta=264.3,280.8
XS Rating Curve= 0 ,0
Exp/Cntr=0.3,0.1

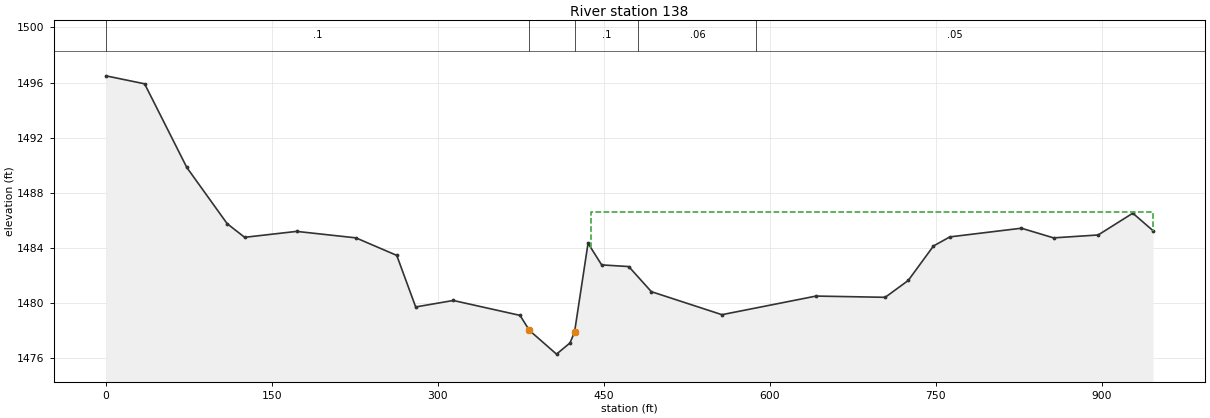
Type RM Length L Ch R = 1 ,138     ,,,
XS GIS Cut Line= 4
2482981.29673873612810.9576097922482755.88293691613078.843016446
2482714.98739833613281.4679123132482964.23809767613580.958564469
#Sta/Elev= 30
       0 1496.49      35 1495.91    73.1 1489.85   109.6 1485.77   125.4 1484.78
   172.4 1485.21     226 1484.74   262.9 1483.47     280 1479.73     314  1480.2
   374.3 1479.12   382.8 1478.03   407.3 1476.31   419.5 1477.12   423.6 1477.91
   435.8 1484.35   448.1 1482.78   472.6 1482.66     493 1480.84   556.8 1479.17
   641.9 1480.52   704.4 1480.43   725.2 1481.65     748 1484.15   762.8 1484.81
   827.5 1485.44   856.6 1484.74   896.9 1484.95   928.2 1486.53   946.5 1485.26
#Mann= 5 ,-1 , 0
       0      .1       0   382.8    .045       0   423.6      .1       0
  481.29     .06       0  587.91     .05       0
#XS Ineff= 2 , 0
                          438.56         1486.61
Permanent Ineff=
       F       F
Bank Sta=382.8,423.6
XS Rating Curve= 0 ,0
Exp/Cntr=0.3,0.1
LCMann Table=0

Chan Stop Cuts=-1
Use User Specified Reach Order=0
Composite Channel Slope=5